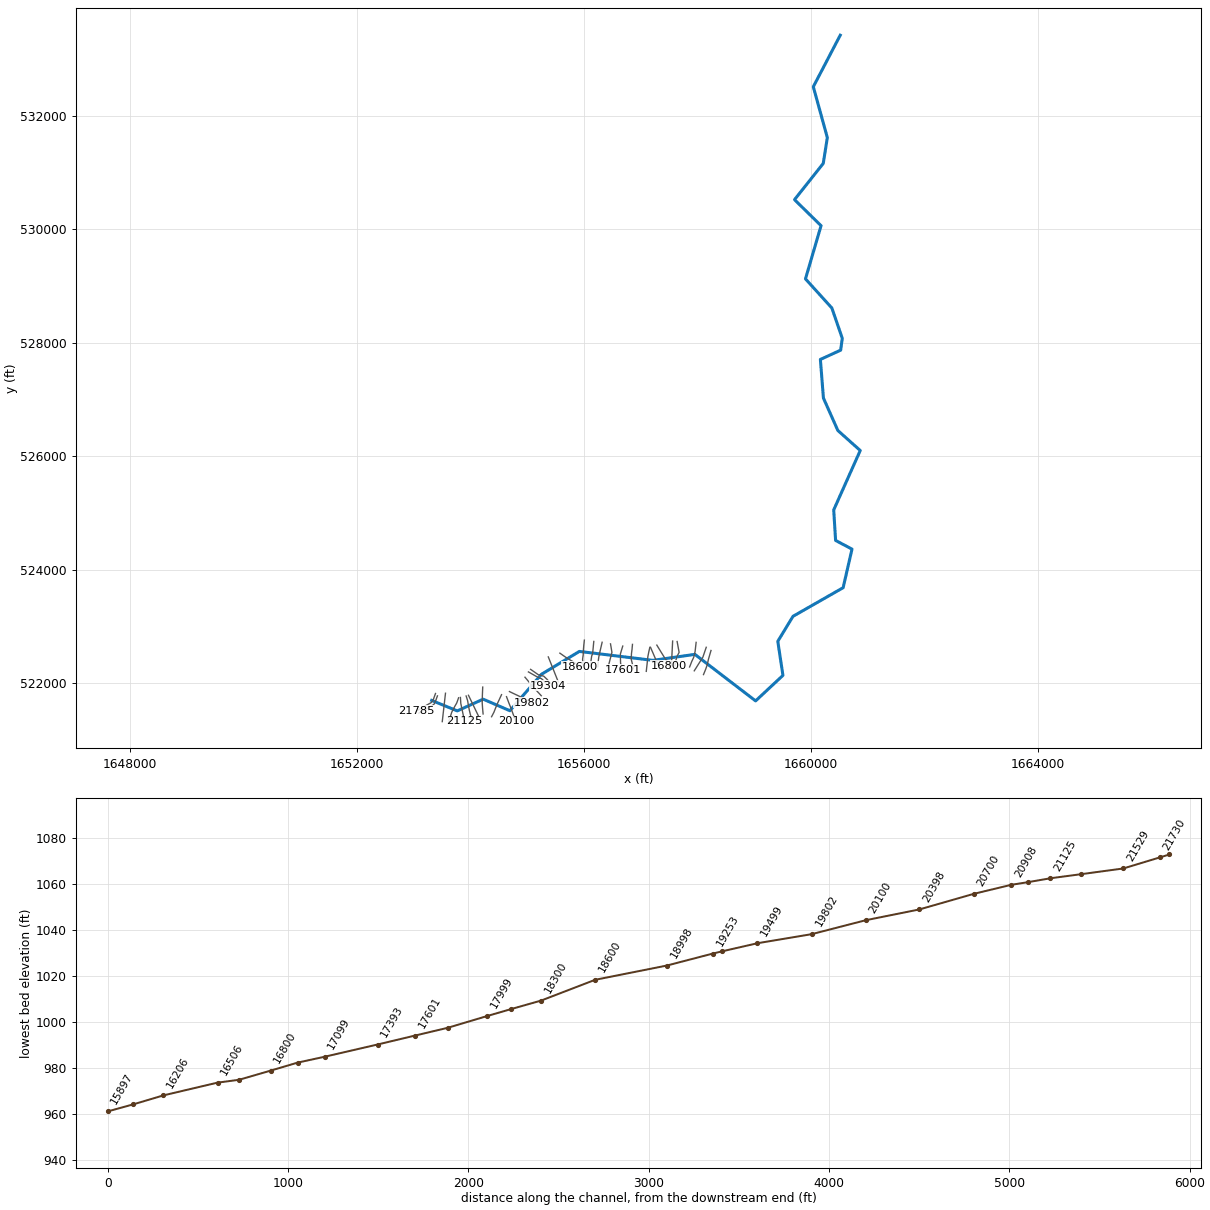
--- StullRn.prj (project) ---

Proj Title=StullRn
Current Plan=p01
Default Exp/Contr=0,0
English Units
Geom File=g01
Flow File=f01
Plan File=p01
BEGIN DESCRIPTION:
---------- MODELED AS PART OF WVEM CTP PROGRAM, 2025----------
Stream Name: Stull Run
Flood Zone: AFH
Marshall County, WV
HEC-RAS Version: RAS 6.6
Vertical Datum: NAVD88
Projection: NAD 1983 StatePlane West Virginia N FIPS 4701 (US Feet)
Terrain: 1-meter West Virginia FEMA R3 South Central (collected 2018-2019)
Land Use: 2024 NLCD
Hydrologic Method:
Duda et al., "Estimation of magnitude and frequency of floods for rural, unregulated streams in and near Virginia and West Virginia." September 8, 2025.
Additional Model Notes:
None
END DESCRIPTION:
DSS Export Rating Curves= 0
DSS Export Rating Curve Sorted= 0
DSS Export Volume Flow Curves= 0
DXF OffsetX= 0
DXF OffsetY= 0
DXF ScaleX= 0
DXF ScaleY= 0

--- StullRn.p01 (plan) ---

Plan Title=Floodplain
Program Version=6.60
Short Identifier=Floodplain
Geom File=g01
Flow File=f01
Subcritical Flow
K Sum by GR= 0
Std Step Tol= 0.01
Critical Tol= 0.01
Num of Std Step Trials= 20
Max Error Tol= 0.3
Flow Tol Ratio= 0.001
Split Flow NTrial= 30
Split Flow Tol= 0.02
Split Flow Ratio= 0.02
Log Output Level= 0
Friction Slope Method= 1
Unsteady Friction Slope Method= 2
Unsteady Bridges Friction Slope Method= 1
Parabolic Critical Depth
Global Vel Dist= 0 , 0 , 0
Global Log Level= 0
CheckData=False
Encroach Param=-1 ,0,0, 0
Flow Ratio Tolerance=0.1
Flow Ratio Min Ratio=0.5
Flow Ratio Max Ratio=4
Flow Ratio Max Iterations= 10
Mapping Interval=1HOUR
Computation Time Step Use Courant=        0
Computation Time Step Use Time Series=    0
Computation Time Step Count To Double=0
Computation Time Step Max Doubling=0
Computation Time Step Max Halving=0
Computation Time Step Residence Courant=0
Run HTab= 0
Run UNet= 0
Run Sediment= 0
Run PostProcess= 0
Run WQNet= 0
Run RASMapper=-1
UNET Theta= 0
UNET Theta Warmup= 0
UNET ZTol= 0
UNET ZSATol= 0
UNET MxIter= 0
UNET Max Iter WO Improvement= 0
UNET MaxInSteps= 0
UNET DtIC= 0
UNET DtMin= 0
UNET MaxCRTS= 0
UNET WFStab= 0
UNET SFStab= 0
UNET WFX= 1
UNET SFX= 1
UNET Gravity=32.17405
UNET 1D Methodology=Finite Difference
UNET DSS MLevel= 1
UNET Pardiso=0
UNET DZMax Abort= 0
UNET Use Existing IB Tables= 0
UNET Froude Reduction=False
UNET Froude Limit= 0
UNET Froude Power= 0
UNET D1 Cores= 0
UNET WindReference=Eulerian
UNET WindDragFormulation=Hsu (1988)
UNET D2 Coriolis=0
UNET D2 Cores= 0
UNET D2 Theta= 1
UNET D2 Theta Warmup= 1
UNET D2 Z Tol= 0.01
UNET D2 Volume Tol= 0.01
UNET D2 Max Iterations= 20
UNET D2 Advanced Convergence=0
UNET D2 WS Max Tol=0.15
UNET D2 WS RMS Tol=0.002
UNET D2 WS Stall Tol=1
UNET D2 Equation= 0
UNET D2 RampUpFraction=0.1
UNET D2 TimeSlices= 1
UNET D2 Turbulence Formulation=Non-Conservative (original)
UNET D2 Eddy Viscosity=0.3
UNET D2 Transverse Eddy Viscosity=0.1
UNET D2 Smagorinsky Mixing=0
UNET D2 BCVolumeCheck=0
UNET D2 Cores=0
UNET D2 SolverType=PARDISO (Direct)
UNET D2 Minimum Iterations= 3
UNET D2 Maximum Iterations= 30
UNET D2 Restart Number= 10
UNET D2 Relaxation Coeff=1.3
UNET D2 SOR Precondition Iterations= 10
UNET D2 ILUT Maximum Fill= 8
UNET D2 ILUT Tolerance=1E-08
UNET D2 Convergence Tolerance=0.00001
PS Theta= 1
PS WS Tol= 0.01
PS Volume Tol= 0.01
PS Max Iterations= 20
PS Equation= 0
PS Advance Time Step=-1
PS Target Courant=0.9
PS Time Slices= 1
PS Iterate With 2D=0
PS Project Initial WSE from DS=-1
PS Ramp Up Initial WSE from US=-1
PS Cores=0
UNET D1D2 MaxIter= 0
UNET D1D2 ZTol=0.01
UNET D1D2 QTol=0.1
UNET D1D2 MinQTol=1
Write IC File= 0
Write IC File at Fixed DateTime=0
Write IC File at Sim End=0
Echo Input=False
Echo Parameters=False
Echo Output=False
Write Detailed= 0
HDF Write Warmup=0
HDF Write Time Slices=0
HDF Flush=0
HDF Compression= 1
HDF Chunk Size= 1
HDF Spatial Parts= 1
HDF Use Max Rows=0
HDF Fixed Rows= 1
Calibration Method= 0
Calibration Iterations= 20
Calibration Max Change=0.05
Calibration Tolerance=0.2
Calibration Maximum=1.5
Calibration Minimum=0.5
Calibration Optimization Method= 1
WQ AD Non Conservative
WQ ULTIMATE=-1
WQ Max Comp Step=1HOUR
WQ Output Interval=15MIN
WQ Output Selected Increments= 0
WQ Create Restart=0
WQ Fixed Restart=0
WQ System Summary=0
WQ Write To DSS=0
Sorting and Armoring Iterations= 10
XS Update Threshold= 0.02
Bed Roughness Predictor= 0
Processes Affected by Predictor=Sediment Only
Hydraulics Update Threshold= 0.02
Energy Slope Method= 1
Volume Change Method= 1
Sediment Retention Method= 0
Sediment TS Multiplier= 1
Warm Up Method= 0
XS Weighting Method= 0
Number of US Weighted Cross Sections= 1
Number of DS Weighted Cross Sections= 1
Upstream XS Weight=0
Main XS Weight=1
Downstream XS Weight=0
Number of DS XS's Weighted with US Boundary= 1
Upstream Boundary Weight= 1
Weight of XSs Associated with US Boundary= 0
Number of US XS's Weighted with DS Boundary= 1
Downstream Boundary Weight= 0.5
Weight of XSs Associated with DS Boundary= 0.5
Percentile Method= 0
Sediment Output Level= 3
Mass or Volume Output= 0
Output Increment Type= 1
Profile and TS Output Increment= 1
Transport Output Increment 1
XS Output Flag= 0
XS Output Increment= 10
Read HDF5 Sediment Hotstart= 0
Sediment Hotstart Type= 0
Write Gradation File= 0
Read Gradation Hotstart= 0
Write HDF5 File= 1
Write Binary Output= 1
Write DSS Sediment File= 0
DSS Sediment Output Type= 1
SV Curve= 0
Specific Gage Flag= 0
Subcell Erosion Methods= 0
Subcell Deposition Methods= 0
Advection Scheme= 1
Matrix Solver= 0
Implicit Weighting Factor= 1
Maximum Outer Loop Convergence Iterations= 5
Convergence Maximum Absolute= 0.001
Convergence RMSE= 0.0001
Grain Fractions Max Abs Error= 0.001
Max Subgrid Regions= 1
Max Subgrid Length Scale= 3.402823E+38
Initial Layer Thickness= 3
Min Layer Thickness= 0.1
Max Layer Thickness= 6
Number of Layers= 5

--- StullRn.f01 (steady flow) ---

Flow Title=Flow
Program Version=6.60
Number of Profiles= 1
Profile Names=P100yr
River Rch & RM=StullRn,Main,21785
     854
River Rch & RM=StullRn,Main,16206
     952
River Rch & RM=StullRn,Main,15002
     953
River Rch & RM=StullRn,Main,14582
    1610
River Rch & RM=StullRn,Main,13200
    1830
River Rch & RM=StullRn,Main,5854
    2050
Boundary for River Rch & Prof#=StullRn,Main            , 1
Up Type= 0
Dn Type= 3
Dn Slope=0.005945
DSS Import GetInterval= 0
DSS Import GetPeak= 0
DSS Import FillOption= 0

--- StullRn.g01 (geometry) ---

Geom Title=Geometry
Program Version=6.60

River Reach=StullRn         ,Main
Reach XY= 30
1653317.30898294521697.240122176     1653768.554      521513.064
     1654224.641      521719.327     1654695.212      521515.754
     1655249.668      522156.652     1655918.944      522560.597
     1657214.245      522403.171     1657953.977      522508.656
     1659023.788       521688.78     1659505.271      522138.437
     1659414.652      522738.615     1659682.377      523178.528
      1660565.97      523683.264     1660721.792      524363.017
     1660432.717      524515.624     1660399.939      525053.677
      1660867.11      526099.583     1660472.584      526452.502
      1660218.74      527022.911     1660164.899      527704.013
     1660521.998       527867.56     1660550.822      528076.063
     1660367.263      528609.655     1659902.347      529123.494
     1660176.861      530060.088     1659709.127       530518.81
     1660215.503      531156.858      1660287.45       531611.54
     1660040.262      532507.609     1660514.928      533415.947

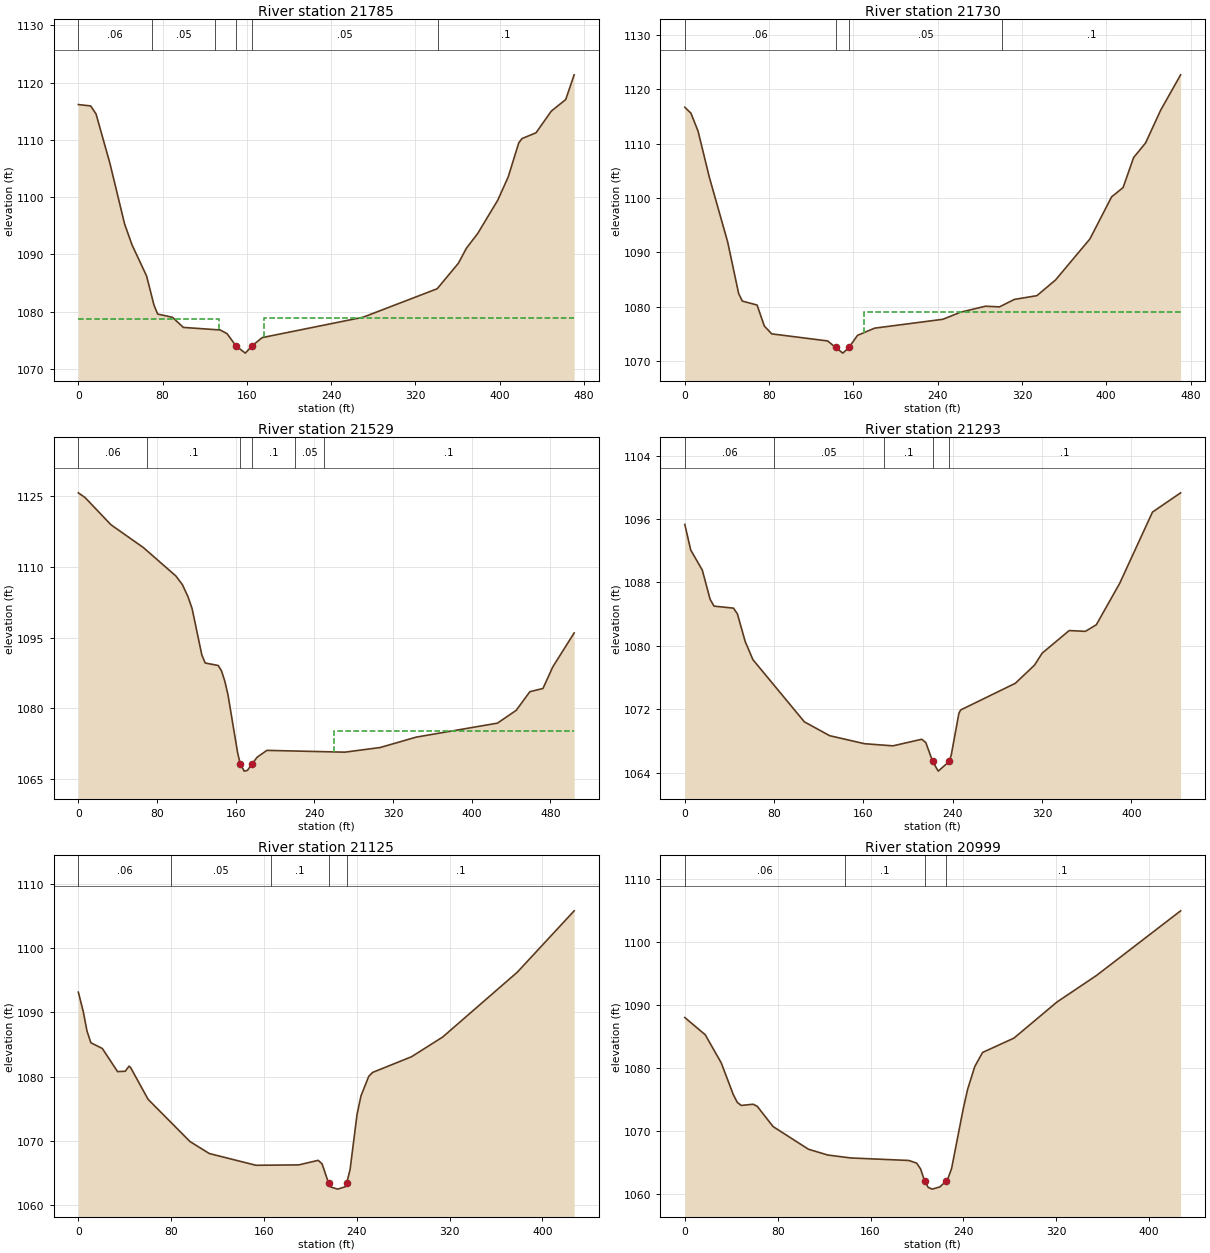
Type RM Length L Ch R = 1 ,21785   ,54,54.1,54.1
XS GIS Cut Line= 4
1653384.89504711521819.5826072681653336.91831443521686.822531296
1653308.47326048521658.9220267821653056.52054441521516.133963324
#Sta/Elev= 30
       0 1116.18    11.7 1115.94    16.8 1114.55      30 1105.91    43.9 1095.34
    50.9 1091.71    64.8 1086.24    71.8 1081.17    75.3  1079.6    89.3 1079.04
    99.7 1077.27   134.7 1076.82   141.2 1076.17  149.611074.047   158.5 1072.78
  164.831074.045   174.5 1075.49   270.3 1079.05   340.6 1084.02   360.8 1088.49
   368.3 1091.09   379.1 1093.68   398.1 1099.49     408 1103.54     418 1109.48
   421.1 1110.24   434.4 1111.25   448.9 1115.03   462.6 1117.06   470.6 1121.37
#Mann= 6 ,-1,0
       0     .06       0      70     .05       0     130     .06       0
  149.61    .045       0  164.83     .05       0  341.01      .1       0
#XS Ineff= 2 , 0
          133.49 1078.79  176.63         1078.87
Permanent Ineff=
       F       F
Bank Sta=149.61,164.83
XS Rating Curve= 0 ,0
Exp/Cntr=0.3,0.1

Type RM Length L Ch R = 1 ,21730   ,195,201.8,204.1
XS GIS Cut Line= 4
1653418.64984444521777.1436565291653370.67311177521644.383580557
1653342.22805782521616.4830760431653090.27534175521473.695012585
#Sta/Elev= 30
       0 1116.68     5.8  1115.6    12.6 1112.29    23.2 1103.89    40.7 1091.93
    51.1 1082.46    54.6 1081.06    68.6 1080.34    75.5 1076.47    82.5 1075.04
   135.6 1073.74  143.041072.554     150  1071.5  155.871072.553   163.9 1074.76
   180.2 1076.09     245 1077.72   261.7 1079.02   285.4 1080.12   298.7    1080
   312.8 1081.37   334.2 1082.06   351.9 1084.95   384.5 1092.48   405.1 1100.22
     416 1101.93     426 1107.44   437.3 1110.11   451.7 1116.16   470.6 1122.64
#Mann= 4 ,-1,0
       0     .06       0  143.04    .045       0  155.87     .05       0
  301.01      .1       0
#XS Ineff= 2 , 0
                          170.04         1078.97
Permanent Ineff=
       F       F
Bank Sta=143.04,155.87
XS Rating Curve= 0 ,0
Exp/Cntr=0.3,0.1

Type RM Length L Ch R = 1 ,21529   ,230.7,236.1,226.7
XS GIS Cut Line= 2
1653560.74102555521824.3836953611653503.81070166521323.476722769
#Sta/Elev= 30
       0 1125.69     6.8  1124.7    33.2 1118.92    66.2 1114.08    99.2 1108.06
   105.8 1106.23   111.5 1103.67   115.7 1101.12   125.6  1091.3     129 1089.62
   142.2 1089.09   145.5 1087.98   148.8 1085.87   152.1 1082.93     162 1070.53
  164.561068.296   168.6  1066.7   171.9 1066.85  176.871068.297   181.8 1069.65
   191.7  1071.1   270.9 1070.72   306.8  1071.7   343.6 1073.91   426.1 1076.87
   445.2 1079.59   459.1 1083.54   472.4 1084.22   482.4 1088.81   504.1 1095.99
#Mann= 6 ,-1,0
       0     .06       0      70      .1       0  164.56    .045       0
  176.87      .1       0     220     .05       0     250      .1       0
#XS Ineff= 2 , 0
                          260.36         1075.15
Permanent Ineff=
       F       F
Bank Sta=164.56,176.87
XS Rating Curve= 0 ,0
Exp/Cntr(USF)=0,0
Exp/Cntr=0.3,0.1

Type RM Length L Ch R = 1 ,21293   ,162.3,168.1,172.4
XS GIS Cut Line= 6
1653791.56859709521743.8846313361653758.75960758521652.152531341
1653718.23705085521581.8239318431653671.85164492521491.775555506
1653648.51704593521419.6625107531653619.56861301521336.128557086
#Sta/Elev= 30
       0 1095.32     5.3  1092.1    15.7 1089.55    22.7 1085.87    26.2 1085.01
    43.6 1084.76    47.1 1084.04    54.1 1080.55      61 1078.26   107.1 1070.41
   129.8 1068.66     161 1067.65   186.4 1067.38   212.2 1068.21   215.9 1067.79
  222.011065.407     227 1064.19   236.81065.407   238.7 1066.25   245.5 1071.48
   247.1 1071.91     296 1075.27   313.2 1077.56   320.1 1079.08   344.3 1081.93
   358.8 1081.83   368.6 1082.66   389.6 1087.91   418.9 1096.88   444.1 1099.31
#Mann= 5 ,-1,0
       0     .06       0      80     .05       0  178.59      .1       0
  222.01    .045       0   236.8      .1       0
Bank Sta=222.01,236.8
XS Rating Curve= 0 ,0
Exp/Cntr(USF)=0,0
Exp/Cntr=0.3,0.1

Type RM Length L Ch R = 1 ,21125   ,125.3,125.7,124.5
XS GIS Cut Line= 3
1653823.77441619521749.6958124661653830.58869475521643.695923681
1653896.46005421521329.481967639
#Sta/Elev= 30
       0 1093.16     4.2 1090.18     7.5 1087.08    10.8 1085.27    20.7 1084.37
    33.8 1080.77    40.4 1080.82    43.7 1081.62      45 1081.42    60.1 1076.45
    96.3 1069.85   112.9 1067.99   153.1 1066.16     190 1066.22   206.7 1066.93
   210.1 1066.37   215.6  1063.4   217.5 1062.78   223.5 1062.44   230.2 1062.82
  231.281063.378   234.2  1065.5   240.2  1074.1   243.6 1076.99   250.3 1080.04
   253.6 1080.64   287.2 1083.09     314 1086.16   378.3 1096.27   427.3 1105.84
#Mann= 5 ,-1,0
       0     .06       0      80     .05       0  166.22      .1       0
   215.6    .045       0  231.28      .1       0
Bank Sta=215.6,231.28
XS Rating Curve= 0 ,0
Exp/Cntr(USF)=0,0
Exp/Cntr=0.3,0.1

Type RM Length L Ch R = 1 ,20999   ,89.2,91.1,93.6
XS GIS Cut Line= 6
1653924.55783242521775.4124554251653951.09091584521691.598974749
1653963.30316176521617.6293064211653981.98389867521519.129503429
1654000.19777301521445.7438234241654025.71084534521361.193795666
#Sta/Elev= 30
       0 1088.03    17.6 1085.29    31.4 1080.81    41.7  1075.8    45.2 1074.53
    48.6 1074.04    58.9 1074.23    62.4  1073.9    76.1 1070.67   106.5 1067.07
   123.1 1066.15     143 1065.68     193 1065.28   199.7 1064.86   203.1 1063.94
   206.71061.951   209.7 1060.99   213.1 1060.72   219.8 1061.08  224.771061.952
   226.8 1062.48   229.8 1063.99   239.8 1073.46   243.6 1076.59   249.8 1080.24
   256.5 1082.47   283.5 1084.75   320.6  1090.5   354.7 1094.73   427.1 1105.01
#Mann= 4 ,-1,0
       0     .06       0  137.91      .1       0   206.7    .045       0
  224.77      .1       0
Bank Sta=206.7,224.77
XS Rating Curve= 0 ,0
Exp/Cntr(USF)=0,0
Exp/Cntr=0.3,0.1

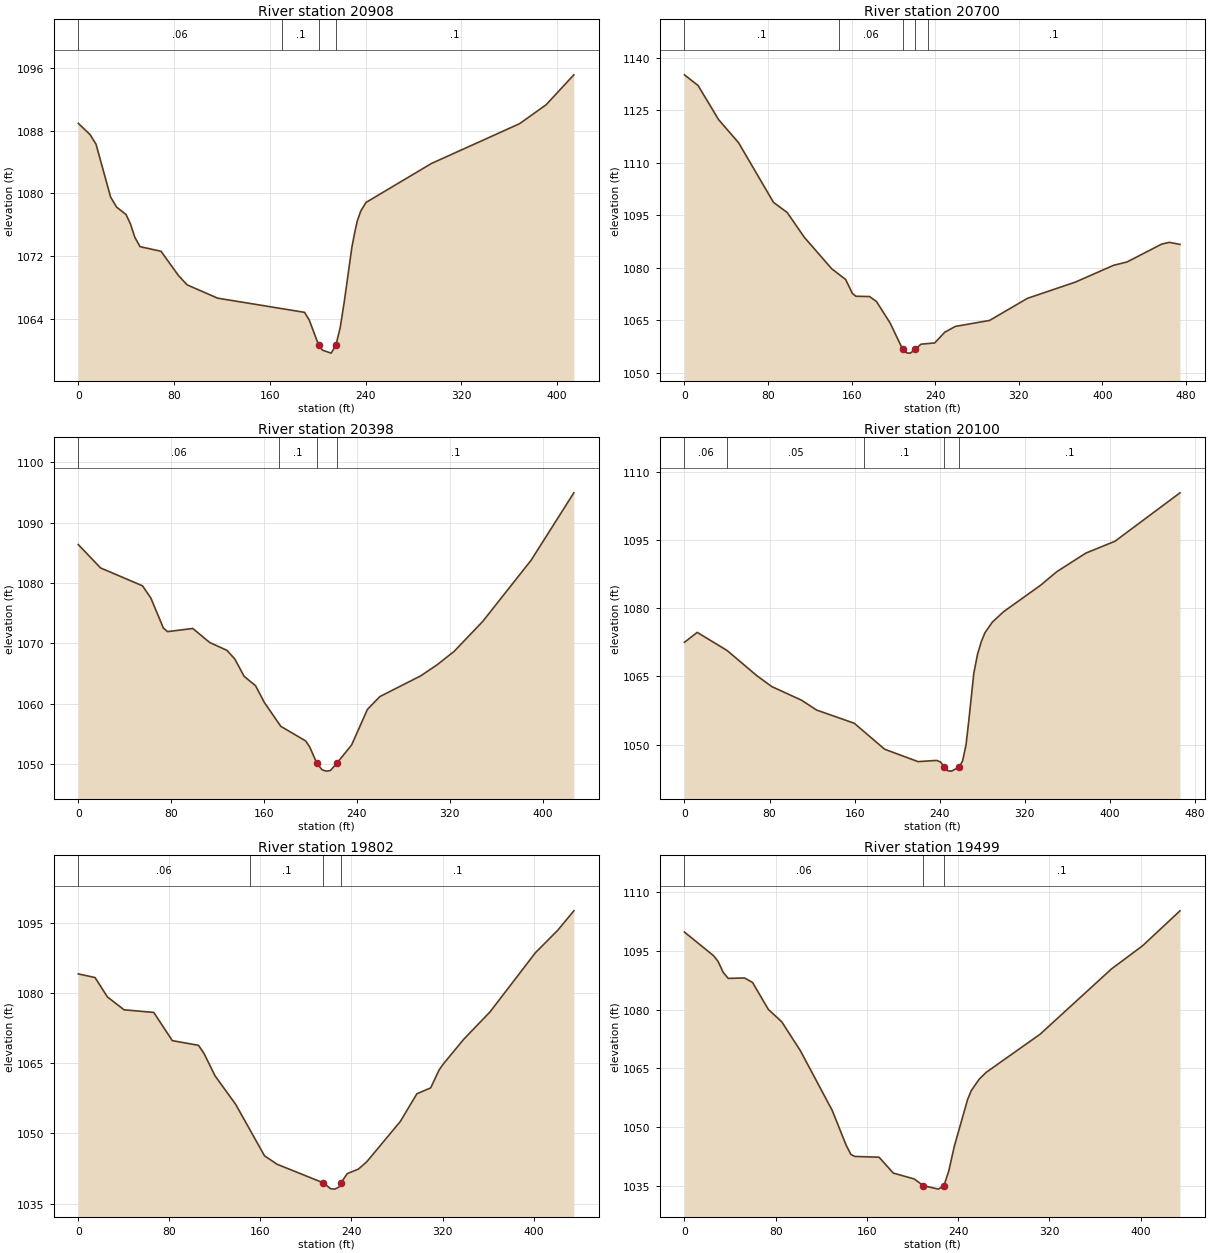
Type RM Length L Ch R = 1 ,20908   ,207.5,208.1,202.1
XS GIS Cut Line= 2
1653965.59647198521788.0062660981654145.49342609521415.265228605
#Sta/Elev= 30
       0 1088.94     9.8 1087.51    14.8 1086.28      27 1079.52      32 1078.24
    39.9 1077.29    43.6 1076.08    47.2 1074.39    51.6 1073.19    69.1  1072.6
    83.7 1069.49    90.9 1068.31   116.4 1066.61     189  1064.8   192.9 1063.81
  200.891060.565   203.9 1059.97   211.2 1059.59  215.081060.584   218.7  1062.8
   222.1 1066.11   228.5 1073.11     231 1075.09     233 1076.47   235.9 1077.73
   240.3 1078.84   294.9 1083.81   368.6  1088.9   390.7 1091.31   413.9 1095.14
#Mann= 4 ,-1,0
       0     .06       0     170      .1       0  200.89    .045       0
  215.08      .1       0
Bank Sta=200.89,215.08
XS Rating Curve= 0 ,0
Exp/Cntr(USF)=0,0
Exp/Cntr=0.3,0.1

Type RM Length L Ch R = 1 ,20700   ,301.3,301.8,295.7
XS GIS Cut Line= 6
1654216.70521401521932.2933752541654212.90338434 521844.74794668
1654209.85680251521769.6568894981654207.63928726521653.892029166
 1654214.0303506521560.5569140021654223.34168367521458.877655417
#Sta/Elev= 30
       0 1135.07      13 1132.04    32.7 1122.28    51.8  1115.7    85.2 1098.68
    98.3 1095.79   114.8 1088.68     141 1079.71   154.2  1076.7   160.7 1072.72
     164 1071.89   177.1 1071.81   183.7 1070.41   196.8 1064.27  208.941056.698
   212.8 1055.72   216.2 1055.66  220.741056.699   226.3 1058.21   239.5 1058.57
     249  1061.6   259.2 1063.28     292 1064.99   328.2 1071.29   374.2 1075.94
   410.5  1080.7   423.6 1081.68   456.7 1086.77     464 1087.27   474.2 1086.68
#Mann= 5 ,-1,0
       0      .1       0  147.63     .06       0  208.94    .045       0
  220.74     .06       0  232.78      .1       0
Bank Sta=208.94,220.74
XS Rating Curve= 0 ,0
Exp/Cntr(USF)=0,0
Exp/Cntr=0.3,0.1

Type RM Length L Ch R = 1 ,20398   ,290,297.8,300.8
XS GIS Cut Line= 6
1654547.94667751521798.976056591 1654511.3640735521719.238027096
1654479.46945226521651.0331110061654441.14111684521558.564463928
1654413.69563368521488.7588292511654372.82399626521410.028343678
#Sta/Elev= 30
       0 1086.35    19.2 1082.48    55.3 1079.53    62.5 1077.49    73.3 1072.53
    76.9 1071.95    98.6 1072.47   113.1 1070.16     128 1068.85   134.8 1067.42
   142.8 1064.56   152.7 1062.99   160.2 1060.24   174.4 1056.28   195.8 1053.87
   199.3 1052.87  205.531050.152     210 1049.09   213.5 1048.87   217.1 1048.97
  222.591050.153   235.4  1053.2     249 1059.08   259.7  1061.2     295 1064.64
   309.1 1066.47   323.7 1068.68   348.3 1073.63     390 1083.76   426.8 1094.91
#Mann= 4 ,-1,0
       0     .06       0  173.02      .1       0  205.53    .045       0
  222.59      .1       0
Bank Sta=205.53,222.59
XS Rating Curve= 0 ,0
Exp/Cntr(USF)=0,0
Exp/Cntr=0.3,0.1

Type RM Length L Ch R = 1 ,20100   ,290,298.3,301.4
XS GIS Cut Line= 6
1654635.82904768521763.3022434261654677.48447618521651.698135927
1654709.39582968 521573.759643511654743.67233592521479.817246094
1654769.37832126521409.3603660021654799.25785467521327.119716838
#Sta/Elev= 30
       0 1072.53      12 1074.71      40 1070.74    68.1 1065.17    82.1 1062.78
   110.1 1059.78   124.2 1057.62   159.6 1054.71   188.2 1048.99   219.6 1046.26
   237.1 1046.53   240.6 1046.19  244.321045.124   247.6 1044.24   251.1 1044.17
  258.471045.125   261.5 1046.45   264.7 1049.99   267.3  1055.3     272 1065.71
   275.5 1069.89     279 1072.65   282.5 1074.64   289.5 1076.99   299.9 1079.25
   334.9 1085.11     350 1088.07   377.3 1092.16   404.7 1094.77   465.8 1105.43
#Mann= 5 ,-1,0
       0     .06       0      40     .05       0  169.12      .1       0
  244.32    .045       0  258.47      .1       0
Bank Sta=244.32,258.47
XS Rating Curve= 0 ,0
Exp/Cntr(USF)=0,0
Exp/Cntr=0.3,0.1

Type RM Length L Ch R = 1 ,19802   ,303.4,302.7,298
XS GIS Cut Line= 6
1654687.41982375521853.569779426  1654768.944267521814.202076003
1654840.67148575521780.6526024191654933.85076134521736.277363092
1655000.15213792 521701.213128761655077.39378133521660.092476085
#Sta/Elev= 30
       0 1084.04    14.7 1083.26    25.6 1079.12    40.2 1076.38    66.3 1075.82
    82.6  1069.8   105.6 1068.81   110.6    1067   120.1 1062.31   138.3  1056.2
   163.6 1045.24   174.7 1043.43  215.271039.469   221.7 1038.22   225.4 1038.13
     229 1038.56  230.85 1039.47   236.3 1041.44   246.1  1042.4   253.5 1043.98
   282.9 1052.55   297.5 1058.47   309.6 1059.73   317.1 1063.59   320.8 1064.85
   338.7 1070.11   361.7 1075.92   401.8  1088.6   421.2 1093.33   435.4 1097.49
#Mann= 4 ,-1,0
       0     .06       0  150.53      .1       0  215.27    .045       0
  230.85      .1       0
Bank Sta=215.27,230.85
XS Rating Curve= 0 ,0
Exp/Cntr(USF)=0,0
Exp/Cntr=0.3,0.1

Type RM Length L Ch R = 1 ,19499   ,189.6,195.2,197.8
XS GIS Cut Line= 6
1654961.12793776 522106.386531011655019.17178492522036.540214002
1655069.41085768521975.9481435871655137.44451426521899.445343837
  1655188.400121521844.4133016771655247.84849292521780.209361836
#Sta/Elev= 30
       0 1099.87    25.6 1093.81    29.4 1092.41      34 1089.55    38.4 1088.03
    52.7 1088.13    59.7 1086.99    73.6 1080.07    85.3 1076.93   101.6 1069.56
   129.5  1054.3   141.7 1045.42   145.9 1043.03   149.3 1042.51   170.6 1042.31
   183.1 1038.25   201.4 1036.75  209.321035.058   222.6 1034.15  227.461035.058
   231.7 1038.77   236.6 1045.12   248.2 1057.05   251.4 1059.32   258.4 1062.26
   264.4 1063.98   311.8 1073.76   374.4 1090.46   401.6 1096.36   434.4  1105.3
#Mann= 3 ,-1,0
       0     .06       0  209.32    .045       0  227.46      .1       0
Bank Sta=209.32,227.46
XS Rating Curve= 0 ,0
Exp/Cntr(USF)=0,0
Exp/Cntr=0.3,0.1

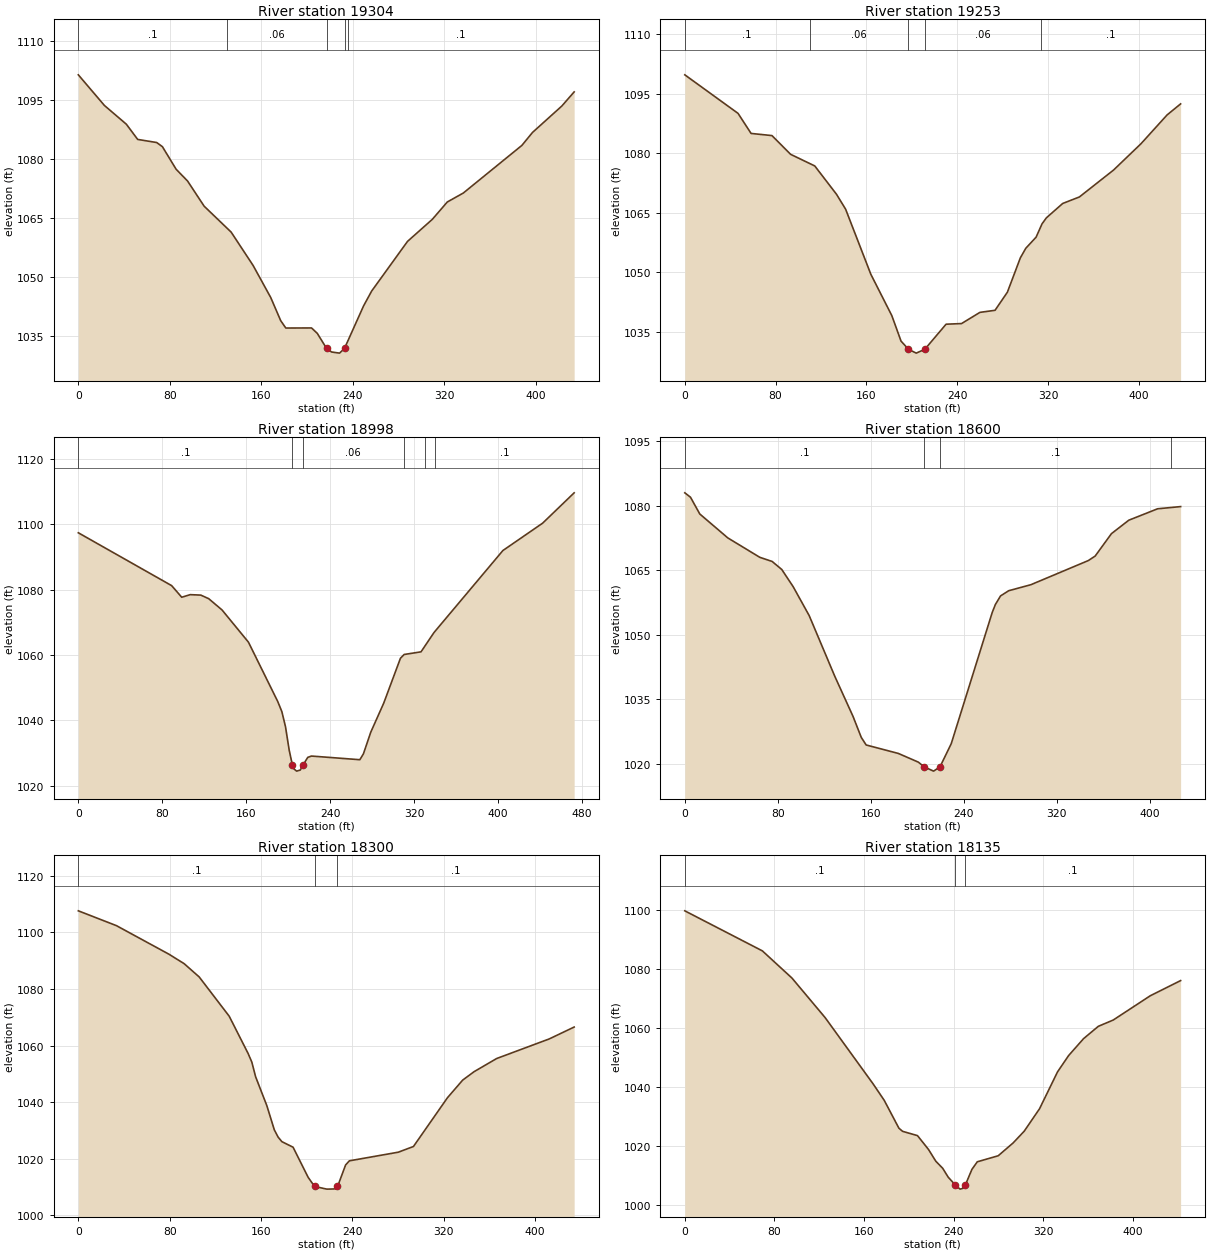
Type RM Length L Ch R = 1 ,19304   ,49.6,51.1,51.3
XS GIS Cut Line= 5
 1655021.7696356522199.7061170321655191.64625723522102.530188139
1655252.14593388522080.0958152081655309.88168623522025.408159359
1655370.38386182521953.762961446
#Sta/Elev= 30
       0 1101.51    22.8 1093.71      42 1088.93    51.9 1085.06    68.5 1084.27
    73.5 1083.22    85.5 1077.47    95.5 1074.47     110 1068.06   133.6 1061.46
   152.8 1052.97   168.2 1044.81   176.9 1038.93   181.4 1037.03   203.9 1037.05
   208.9 1035.68  217.061031.837   221.4 1030.93   228.4 1030.64  232.711031.837
   249.4 1042.67   256.4 1046.42   287.8 1059.09   309.5 1064.71   322.6 1069.13
   336.6 1071.41   387.8 1083.54   397.1 1086.84   422.7 1093.56   433.5 1097.16
#Mann= 5 ,-1,0
       0      .1       0     130     .06       0  217.06    .045       0
  232.71     .06       0  235.71      .1       0
Bank Sta=217.06,232.71
XS Rating Curve= 0 ,0
Exp/Cntr(USF)=0,0
Exp/Cntr=0.3,0.1

Type RM Length L Ch R = 1 ,19253   ,260.7,254.8,248.3
XS GIS Cut Line= 5
1655060.24189754522244.7847865921655196.96079293522149.187797044
1655290.61819582522125.1744847681655348.35394817522070.486828919
1655408.85612376521998.841631006
#Sta/Elev= 30
       0  1099.8    46.9 1090.09    58.4 1085.03    76.8 1084.49    93.2 1079.77
   114.5 1076.84   133.7 1069.68   141.7 1065.93   163.9 1049.54   182.4 1039.11
   190.5  1032.7  197.071030.632   203.9 1029.67  211.431030.633   230.2 1036.96
   243.8 1037.12     260 1039.94   273.3 1040.46   284.2 1045.03   295.6 1053.67
   300.4 1056.09   309.5  1058.9   314.7 1062.24   318.5 1063.75   332.9 1067.38
   347.6 1069.02   377.7  1075.8   401.9 1082.44   424.9  1089.7   436.8 1092.48
#Mann= 5 ,-1,0
       0      .1       0     110     .06       0  197.07    .045       0
  211.43     .06       0  313.51      .1       0
Bank Sta=197.07,211.43
XS Rating Curve= 0 ,0
Exp/Cntr(USF)=0,0
Exp/Cntr=0.3,0.1

Type RM Length L Ch R = 1 ,18998   ,391,397.9,399.8
XS GIS Cut Line= 2
1655372.13920245522463.5824965941655547.14120142522024.835513011
#Sta/Elev= 30
       0 1097.35    88.9 1081.19    98.5 1077.64   106.6 1078.43   116.7 1078.29
   124.2  1077.2   136.9 1073.76   162.1 1063.89   189.9 1045.81   193.9 1042.67
   197.4 1038.02   200.9 1030.87  204.031026.198     205 1025.26     208 1024.46
   211.5 1024.79  213.821026.195   218.6 1028.67   222.1 1029.07   268.2 1027.95
   271.6 1029.73   278.6 1036.35   290.9  1045.2   306.9 1058.97   310.4 1060.13
   326.5 1060.94   338.9 1066.86   404.5 1091.92   442.4  1100.3   472.4 1109.57
#Mann= 6 ,-1,0
       0      .1       0  204.03    .045       0  213.82     .06       0
     310      .1       0     330     .06       0     340      .1       0
Bank Sta=204.03,213.82
XS Rating Curve= 0 ,0
Exp/Cntr(USF)=0,0
Exp/Cntr=0.3,0.1

Type RM Length L Ch R = 1 ,18600   ,305.9,299.8,286.9
XS GIS Cut Line= 6
1655575.86719383522530.2068775891655647.56291659522479.629550919
1655709.48634918522437.1129036691655796.04162225522386.999486834
1655860.53132267522348.6465451721655927.05546784522290.198827416
#Sta/Elev= 30
       0 1082.95     4.9 1081.93    12.9 1078.03      37 1072.47    64.5 1067.96
    75.1    1067    83.4 1065.13    93.2 1061.14     107 1054.41     129 1040.31
   144.7 1030.98   151.8 1026.09     156 1024.33   183.7 1022.36   200.9 1020.34
  205.891019.243     214 1018.25  219.521019.244   229.2 1024.64   264.4  1055.1
   267.1 1056.96   271.6 1058.98   278.6 1060.19   297.7 1061.59   347.1  1067.2
     353 1068.25     367 1073.46   381.9 1076.58   406.7 1079.24   426.5 1079.75
#Mann= 4 ,-1,0
       0      .1       0  205.89    .045       0  219.52      .1       0
   417.9     .06       0
Bank Sta=205.89,219.52
XS Rating Curve= 0 ,0
Exp/Cntr(USF)=0,0
Exp/Cntr=0.3,0.1

Type RM Length L Ch R = 1 ,18300   ,166.8,165.3,160.6
XS GIS Cut Line= 6
1656006.95163351522759.4337813411655997.32205959522672.349309832
  1655991.107177 522597.543029011655986.68526985522497.640341669
1655975.76107909522423.1532859211655984.67051008522327.452033758
#Sta/Elev= 30
       0 1107.65    33.4  1102.4    79.4 1092.29    92.6 1088.97   105.8 1084.27
   132.1 1070.37   148.6 1057.23   151.9 1054.14   155.2 1048.98     165 1038.78
   171.6 1030.17   174.9 1027.62   178.2    1026     188 1024.04   201.2 1013.39
  206.831010.159   217.6 1009.21   224.1 1009.27  226.311010.161   227.4  1010.6
     234 1017.76   237.3 1019.22   280.1 1022.27   293.4 1024.29   323.2 1041.55
   336.5 1047.77   346.4 1050.73   366.2  1055.4   412.3 1062.34   434.1 1066.54
#Mann= 3 ,-1,0
       0      .1       0  206.83    .045       0  226.31      .1       0
Bank Sta=206.83,226.31
XS Rating Curve= 0 ,0
Exp/Cntr(USF)=0,0
Exp/Cntr=0.3,0.1

Type RM Length L Ch R = 1 ,18135   ,133.7,135.6,135.9
XS GIS Cut Line= 5
1656173.20085591522736.3735565261656154.25358378522536.936148955
1656149.75770949522513.5048080441656135.83449222522479.165968946
1656110.91169876522299.323145907
#Sta/Elev= 30
       0 1099.86    69.3 1086.28    95.7 1077.07   125.3 1063.68   168.2 1041.19
   178.1 1035.63   191.2 1026.19   194.5 1025.12   207.8 1023.67   217.6    1019
   224.2 1014.97   230.3 1012.61   235.2  1009.6  241.641006.903   245.8 1005.53
   248.9 1005.86  250.521006.904   256.4 1012.21   261.2 1014.79   279.9 1016.84
   293.2 1021.18   303.1 1025.16   316.8 1032.77   332.9 1045.29   342.8 1050.81
   356.1 1056.53   369.3 1060.71   382.6 1062.84   415.7 1071.07   442.8 1076.21
#Mann= 3 ,-1,0
       0      .1       0  241.64    .045       0  250.52      .1       0
Bank Sta=241.64,250.52
XS Rating Curve= 0 ,0
Exp/Cntr(USF)=0,0
Exp/Cntr=0.3,0.1

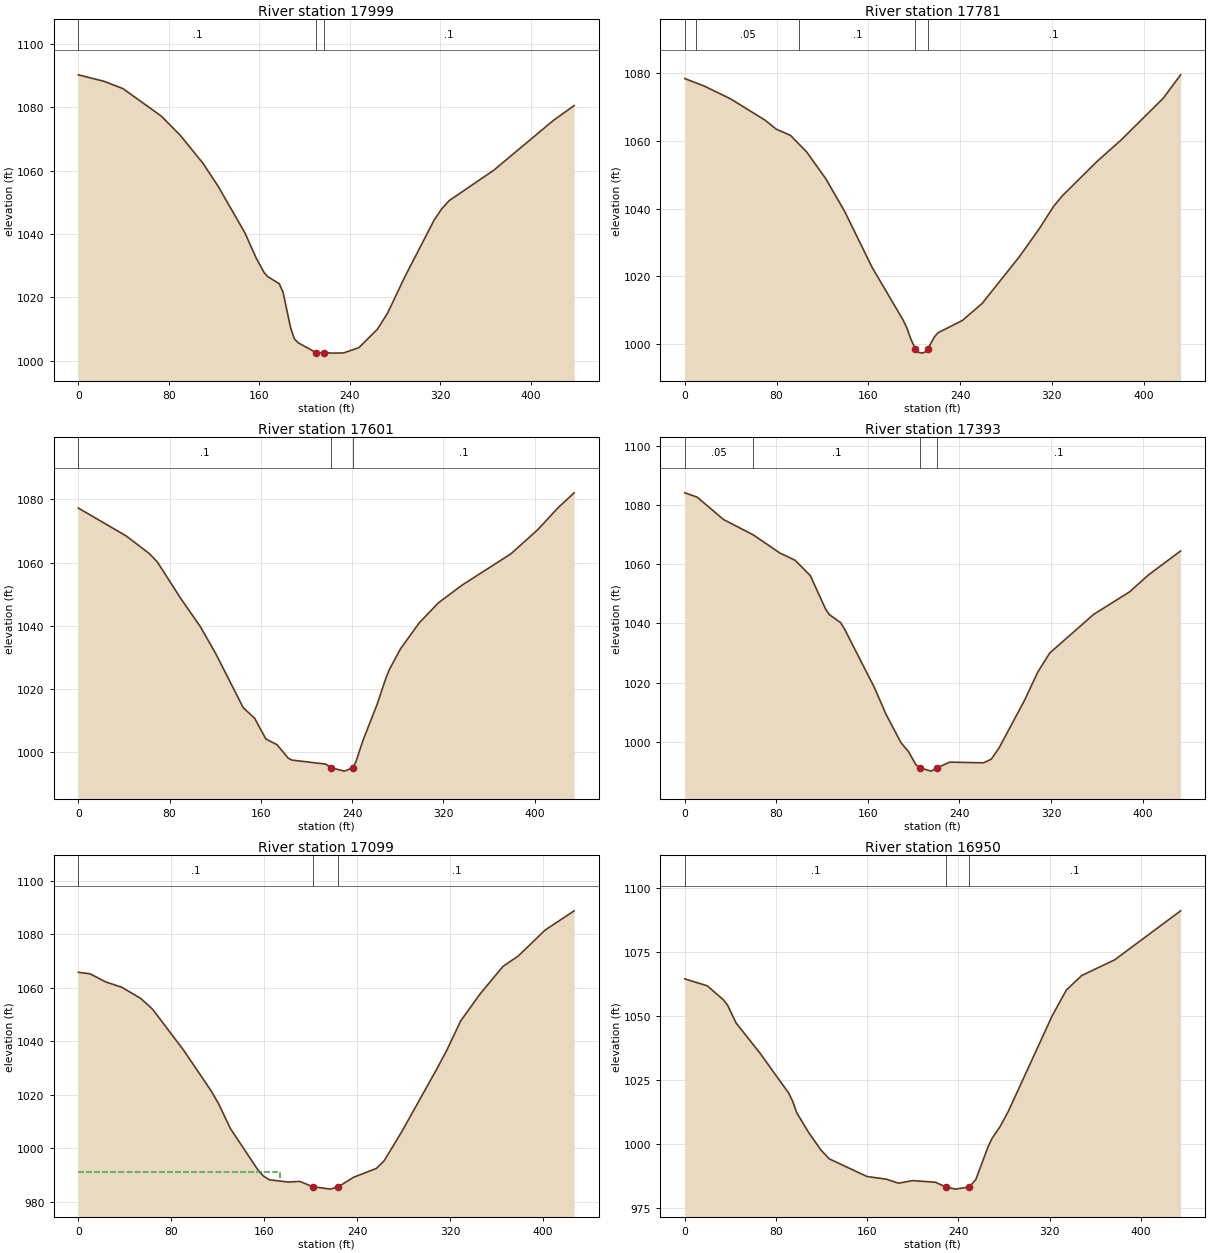
Type RM Length L Ch R = 1 ,17999   ,218,217.8,216.7
XS GIS Cut Line= 6
1656320.19838235522722.1812311711656300.33818585522637.008501261
  1656283.315254 522563.998148591656261.38878867522462.693561167
1656250.99642101522383.2127490041656245.19853234522291.414376169
#Sta/Elev= 30
       0  1090.2    22.6 1088.17    39.4 1085.86    73.1 1077.25      90 1071.17
   110.2 1062.29   123.7 1054.97   147.2 1040.39   157.3 1032.33   164.1  1027.9
   167.4 1026.56   177.5 1024.36   180.9 1021.71   187.6 1010.45   190.9 1006.96
   194.3 1005.71   210.2 1002.59   217.3 1002.59   224.5 1002.44   234.6 1002.51
     248 1004.19   264.3 1009.97   273.3 1015.05   288.5 1026.45   314.4 1044.36
     321 1047.87   327.7 1050.52   367.2 1060.13   419.8 1075.81   438.2 1080.51
#Mann= 3 ,-1,0
       0      .1       0   210.2    .045       0   217.3      .1       0
Bank Sta=210.2,217.3
XS Rating Curve= 0 ,0
Exp/Cntr(USF)=0,0
Exp/Cntr=0.3,0.1

Type RM Length L Ch R = 1 ,17781   ,175.1,180,181.5
XS GIS Cut Line= 3
1656467.84234544522693.5256105231656492.74071274522544.724983163
1656422.45111896522272.205805215
#Sta/Elev= 30
       0  1078.4    16.5 1076.26    39.8 1072.44    69.8 1066.17    79.7 1063.47
    92.1 1061.64   106.3 1056.72     123  1048.8   139.6 1039.05   163.1  1022.8
   190.2 1007.19   193.7 1004.73     197 1001.57  201.02998.5668   203.8  997.58
   207.2  997.34   210.6  997.87  211.86998.5679   217.3 1001.98   220.7 1003.34
   242.1    1007   259.2    1012   291.9  1025.9   308.8 1033.94   321.5 1040.64
   329.1 1043.77   359.6    1054     380 1060.14   417.2 1072.62   432.3 1079.51
#Mann= 5 ,-1,0
       0      .1       0      10     .05       0     100      .1       0
  201.02    .045       0  211.86      .1       0
Bank Sta=201.02,211.86
XS Rating Curve= 0 ,0
Exp/Cntr(USF)=0,0
Exp/Cntr=0.3,0.1

Type RM Length L Ch R = 1 ,17601   ,206.3,208.2,206.8
XS GIS Cut Line= 4
1656683.40480466522654.8912355011656641.29975547522514.541071525
1656644.80850957522352.2611944281656686.91355876522233.840743574
#Sta/Elev= 30
       0 1077.28    41.8 1068.49    62.3 1062.84    69.2 1060.23    89.7 1048.69
   106.9 1039.75   120.6 1031.06   144.5 1014.07   154.5 1010.74   164.3 1004.19
   174.1 1002.36     184  998.07   187.3  997.48   216.8  996.22  221.81995.0251
   233.2  993.99  240.33995.0233   243.1   996.8   249.6 1003.87   261.8  1015.1
   269.3 1023.19   272.6 1026.19   282.4 1032.75   298.8 1040.96   315.6  1047.3
   336.5 1052.93   379.1 1062.79   402.7 1070.47   420.5 1077.42   434.5  1082.1
#Mann= 3 ,-1,0
       0      .1       0  221.81    .045       0  240.33      .1       0
Bank Sta=221.81,240.33
XS Rating Curve= 0 ,0
Exp/Cntr(USF)=0,0
Exp/Cntr=0.3,0.1

Type RM Length L Ch R = 1 ,17393   ,293.4,293.8,293
XS GIS Cut Line= 6
1656854.70584351522684.6589965081656846.93354934522597.235614926
1656837.02641693 522522.821065591656833.10844576522422.303550094
 1656851.5601805522346.6928089261656866.68875918522255.924945846
#Sta/Elev= 30
       0 1084.16    10.8 1082.71    33.8 1075.15      60  1069.9    83.2 1063.79
    96.4 1061.37   109.7 1056.18   122.9 1044.98   126.2 1043.03   136.2 1040.27
   139.5 1038.19   165.9 1018.17   175.8 1009.34   188.9  999.73   195.5  996.67
     202  992.24  205.28991.2352   215.2  990.09  220.71991.2335   231.6  993.13
   261.1   992.9   267.8  994.12   274.6  997.91   296.9 1014.04   308.4 1023.52
   318.9 1030.01   357.3 1043.07   388.7 1050.69   405.3 1056.44   433.3 1064.51
#Mann= 4 ,-1,0
       0     .05       0      60      .1       0  205.28    .045       0
  220.71      .1       0
Bank Sta=205.28,220.71
XS Rating Curve= 0 ,0
Exp/Cntr(USF)=0,0
Exp/Cntr=0.3,0.1

Type RM Length L Ch R = 1 ,17099   ,145.8,149.5,156.1
XS GIS Cut Line= 6
1657159.98312008522631.3110060841657140.69674134522544.882701263
1657125.96317501522470.4602779151657115.60886501522370.989020169
1657107.31557451 522296.452751921657097.83790317522209.489343166
#Sta/Elev= 30
       0  1065.8    10.1 1065.23    23.6  1062.2    37.5 1060.19    53.8 1056.01
    63.9 1052.01    90.8 1036.59   114.2 1021.59   120.9 1016.57   130.9 1007.43
   154.3  992.15   159.1  989.73   164.4  988.25   180.8  987.41   190.7  987.65
  201.78985.6703   217.1  984.76  223.92985.6714   236.9  989.17   256.7  992.52
   263.3  995.36   278.6 1006.32   308.3 1029.39   317.2 1036.63   329.3 1047.68
   345.8 1057.65   365.6    1068   378.8  1071.9   401.9 1081.58   426.9 1088.77
#Mann= 3 ,-1,0
       0      .1       0  201.78    .045       0  223.92      .1       0
#XS Ineff= 2 , 0
          173.63  991.19
Permanent Ineff=
       F       F
Bank Sta=201.78,223.92
XS Rating Curve= 0 ,0
Exp/Cntr(USF)=0,0
Exp/Cntr=0.3,0.1

Type RM Length L Ch R = 1 ,16950   ,148.4,149.8,151.5
XS GIS Cut Line= 2
1657172.77853613522632.9615223791657344.31762544522233.353416616
#Sta/Elev= 30
       0 1064.35    19.7 1061.65      34 1056.12    37.5 1054.12    44.9  1047.2
    66.1 1035.26    91.1 1019.76    94.7 1016.48    98.2 1012.05   108.9 1004.14
   119.6   997.4   126.8  994.02   159.8  987.15   176.8  986.09   187.5  984.53
   199.8  985.54   219.8   984.9  229.03983.0514   237.3  982.21  249.53983.0524
   255.3  985.99     266  998.78   269.6 1002.12   276.7 1006.76   283.9 1012.72
   322.2  1049.9   334.7 1060.02   348.1 1065.66   377.2 1071.84   434.9 1090.95
#Mann= 3 ,-1,0
       0      .1       0  229.03    .045       0  249.53      .1       0
Bank Sta=229.03,249.53
XS Rating Curve= 0 ,0
Exp/Cntr(USF)=0,0
Exp/Cntr=0.3,0.1

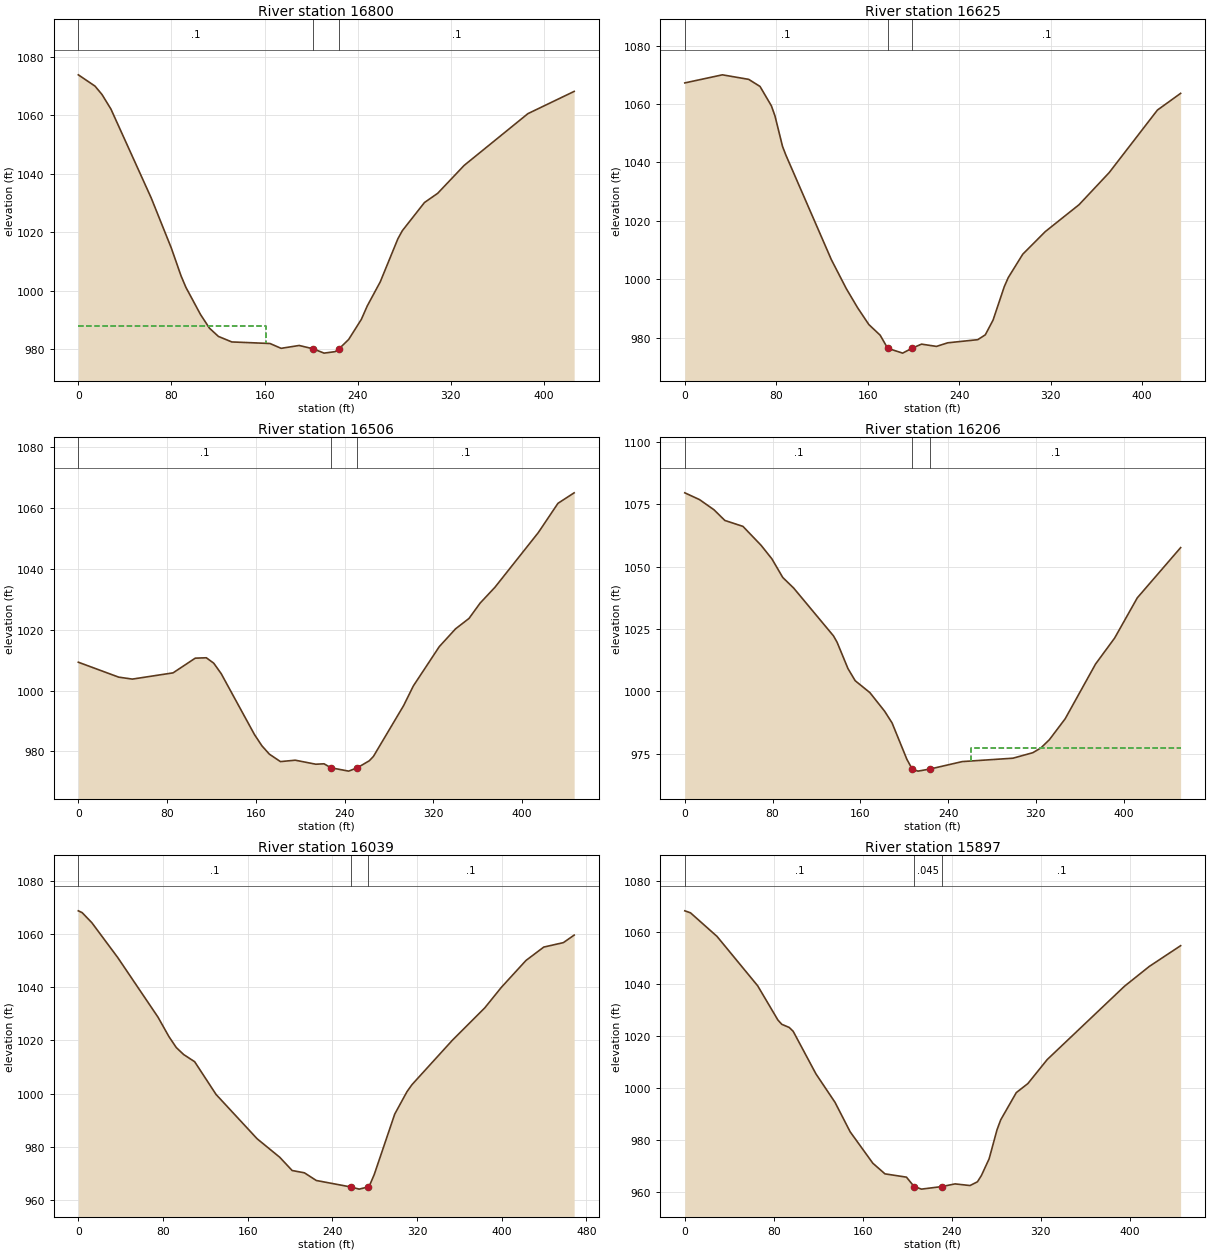
Type RM Length L Ch R = 1 ,16800   ,181.3,175,168.5
XS GIS Cut Line= 6
1657283.59310909522671.550426915 1657329.2465611522596.909171999
1657368.38099726522532.9299692511657421.40877834522448.147330418
1657459.03009418522383.2091400921657496.96013643522303.435677588
#Sta/Elev= 30
       0 1073.89    14.3 1070.04    20.3 1067.18      28 1062.18    62.6 1031.79
    79.9 1014.63    88.2 1005.17    92.4 1001.22   104.9  991.96   112.6  987.27
   120.3  984.44   131.8  982.55   164.6  982.01   174.2  980.36   189.7  981.34
   201.9  980.17   211.1  978.72   220.6  979.23     224980.2096   232.2  983.39
   243.1  990.26   248.2  994.87   259.3 1003.06   274.5 1017.83   278.3 1020.58
   297.3 1030.21   308.7 1033.38   331.4 1042.91   386.2 1060.62   425.9 1068.22
#Mann= 3 ,-1,0
       0      .1       0   201.9    .045       0     224      .1       0
#XS Ineff= 2 , 0
          161.37  987.99
Permanent Ineff=
       F       F
Bank Sta=201.9,224
XS Rating Curve= 0 ,0
Exp/Cntr(USF)=0,0
Exp/Cntr=0.3,0.1

Type RM Length L Ch R = 1 ,16625   ,122.4,119.3,113.8
XS GIS Cut Line= 2
1657562.19232807522742.8973218431657540.31933515522309.643808157
#Sta/Elev= 30
       0 1067.21    32.9 1069.98    55.9 1068.43    65.8 1066.01    75.8 1059.34
    78.9 1055.91    85.5  1045.5    88.3 1042.64   128.2 1006.75   141.3  996.81
   151.2  990.27     161  984.53   170.9  980.89   177.5   976.4   190.6  974.74
  198.68976.3851   207.1  977.82   220.2  977.04     230  978.27   256.3  979.34
   262.9     981   269.7  986.04   279.5  997.47     283 1000.59   295.7  1008.6
   315.4 1016.33     345 1025.56   371.3 1036.52   413.5 1057.92   433.8 1063.64
#Mann= 3 ,-1,0
       0      .1       0   177.5    .045       0  198.68      .1       0
Bank Sta=177.5,198.68
XS Rating Curve= 0 ,0
Exp/Cntr(USF)=0,0
Exp/Cntr=0.3,0.1

Type RM Length L Ch R = 1 ,16506   ,292.9,300,301.2
XS GIS Cut Line= 4
 1657641.1966349 522734.953581421657676.59837232522543.695258078
1657630.85849068522456.1758576781657601.15356263522305.282966387
#Sta/Elev= 30
       0  1009.3    36.4 1004.39    48.7 1003.75    85.4  1005.8   105.4 1010.63
   115.4 1010.76   122.1 1008.97   128.8 1005.54   158.8  985.52   165.5  981.82
   172.2  979.09   182.2  976.63   195.6  977.09   214.1  975.77   221.5  975.91
  227.74974.6007   243.7   973.5   251.5   974.6   262.3   976.9     266  978.32
   293.3  995.07     302 1001.49   325.4 1014.42   340.1 1020.28   352.2 1023.69
   362.2 1028.72   375.6 1033.94   414.7 1051.92   432.4 1061.53     447 1064.98
#Mann= 3 ,-1,0
       0      .1       0  227.74    .045       0   251.5      .1       0
Bank Sta=227.74,251.5
XS Rating Curve= 0 ,0
Exp/Cntr(USF)=0,0
Exp/Cntr=0.3,0.1

Type RM Length L Ch R = 1 ,16206   ,167.2,166.6,161.4
XS GIS Cut Line= 6
1657976.10419126522720.0093194991657966.22363359522633.069204673
1657957.75449042522558.5490125121657934.86739708522460.225390255
 1657898.6981781522382.0716751661657861.19628459522286.882233009
#Sta/Elev= 30
       0 1079.67    13.4 1076.95    26.6 1072.87    36.5 1068.58      53  1066.2
    69.5 1058.62    79.4 1053.15    89.3 1045.68    99.2 1041.45   135.5 1022.25
   138.8 1019.69   148.7 1009.13   155.3 1004.24   168.7  999.46   182.1  992.02
   188.9  987.31   202.4  972.71  207.22968.7986   212.5  967.95  223.53968.7999
   252.9  971.78   299.1  973.14   317.2  975.35   324.5  977.24   332.3  980.57
   346.7  988.98   374.4 1010.96   391.8  1021.4   412.4 1037.51   451.9 1057.67
#Mann= 3 ,-1,0
       0      .1       0  207.22    .045       0  223.53      .1       0
#XS Ineff= 2 , 0
                          261.01          977.26
Permanent Ineff=
       F       F
Bank Sta=207.22,223.53
XS Rating Curve= 0 ,0
Exp/Cntr(USF)=0,0
Exp/Cntr=0.3,0.1

Type RM Length L Ch R = 1 ,16039   ,139.3,142.6,143
XS GIS Cut Line= 3
1658154.35220061522633.5323572231658094.62210454 522459.38968279
1657943.19369199522218.786760627
#Sta/Elev= 30
       0 1068.71     3.6 1068.03    12.8 1064.23    37.2 1051.16    75.2 1028.77
    85.6 1021.41    92.6 1017.27    99.5 1014.67   109.9 1011.97   130.1  999.67
   168.9     983   190.3  976.03     202  971.06   213.6  970.19   224.8  967.31
  257.66964.8515   265.3  964.06   273.4  964.85   275.6   965.9   279.5   969.5
   298.9  992.28   310.5 1000.73   315.2 1003.35   353.5 1020.11   383.9 1032.19
   399.7 1039.97   422.9 1050.05   439.7 1055.08   458.2 1056.75   468.4 1059.58
#Mann= 3 ,-1,0
       0      .1       0  257.66    .045       0   273.4      .1       0
Bank Sta=257.66,273.4
XS Rating Curve= 0 ,0
Exp/Cntr(USF)=0,0
Exp/Cntr=0.3,0.1

Type RM Length L Ch R = 1 ,15897   ,304.1,296.8,280.7
XS GIS Cut Line= 6
1658238.14763042522577.1149202591658213.64899176522493.135101333
 1658192.6483776522421.1506652531658171.19861734522322.944168761
1658142.31678534 522242.057519511658105.96351159522152.374628007
#Sta/Elev= 30
       0 1068.35     5.1 1067.59      29 1058.46    65.5 1039.42    83.7  1026.2
    87.1 1024.59    93.9 1023.33    97.4 1021.87   117.9 1005.41     135  994.46
   148.6   983.1     169  970.96   179.9  966.86   199.2  965.59  206.09 961.963
   212.7  960.97   231.1961.9629   242.9  962.99   256.3  962.35     263   963.8
   266.5  966.17   273.5  972.67   280.6  983.88   283.9  987.69   297.9   998.2
   308.3 1001.69   325.7 1010.96   395.2 1039.27   417.4 1046.88   445.6  1054.9
#Mann= 3 ,-1,0
       0      .1       0  206.09    .045       0   231.1      .1       0
Bank Sta=206.09,231.1
XS Rating Curve= 0 ,0
Exp/Cntr(USF)=0,0
Exp/Cntr=0.3,0.1