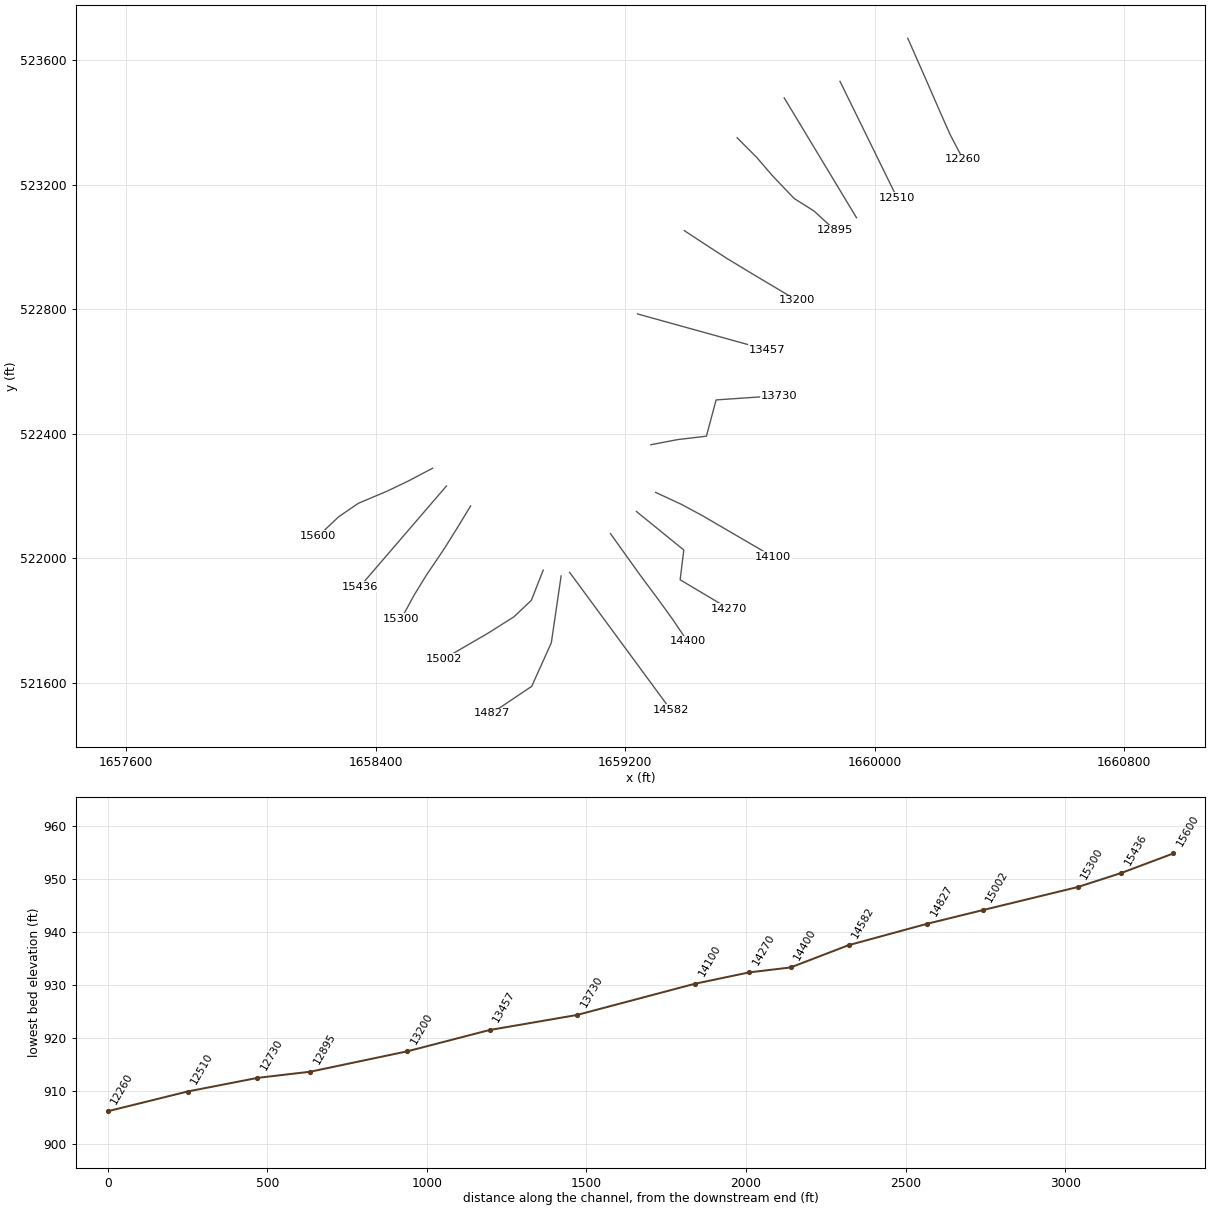
HEC-RAS study StullRn.prj: StullRn

--- StullRn.g01 (geometry) --- (continued)

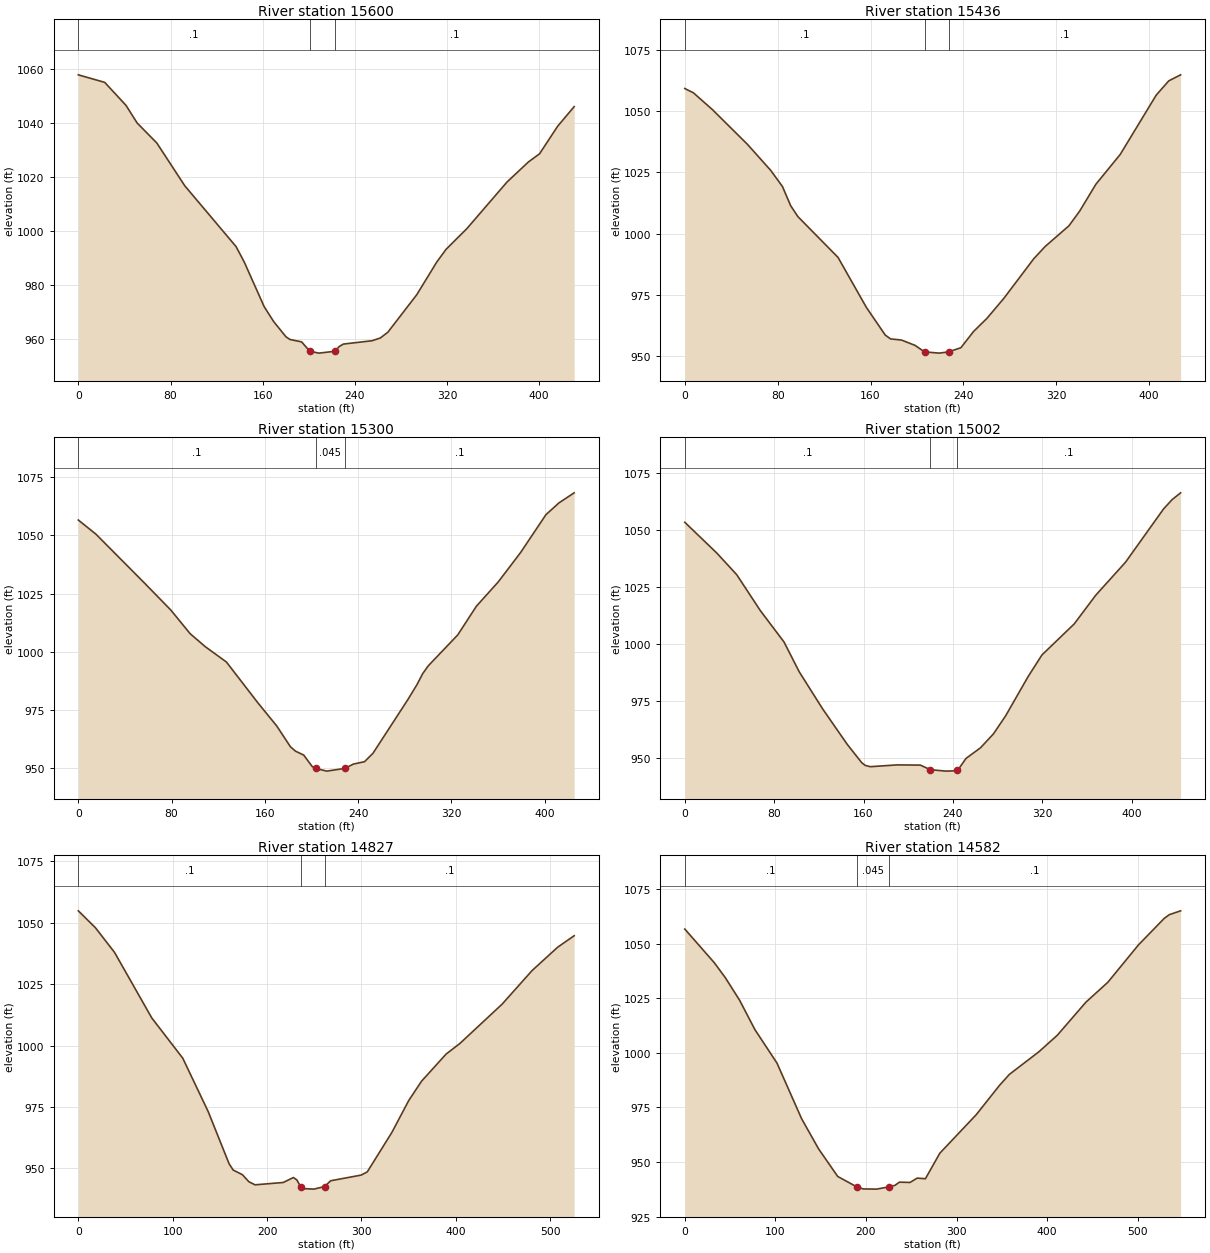
Type RM Length L Ch R = 1 ,15600   ,157.2,163.4,167.2
XS GIS Cut Line= 6
1658582.34871368522289.675206423 1658504.2560221522248.469908252
1658436.16921601522215.9263381661658344.04768109522177.017623335
1658281.14065467 522133.928798751658215.55318743522071.913502842
#Sta/Elev= 30
       0 1057.84    22.9 1055.05    41.4 1046.53    51.1 1039.99    68.1 1032.63
    92.4 1016.78   136.9  994.29     144  988.57   161.3  972.06   169.5  966.57
   180.2  960.92   183.7  959.93   193.8  959.04  200.85 955.572   208.8  954.88
  222.72955.5728   226.5  957.36     230  958.23     255  959.47   262.1  960.49
   268.6   962.6   293.7  976.49   311.1   988.6   319.1  993.27   337.1  1000.9
   371.9 1018.12   390.5 1025.57   400.3 1028.64     416 1038.83   430.3 1046.07
#Mann= 3 ,-1,0
       0      .1       0  200.85    .045       0  222.72      .1       0
Bank Sta=200.85,222.72
XS Rating Curve= 0 ,0
Exp/Cntr(USF)=0,0
Exp/Cntr=0.3,0.1

Type RM Length L Ch R = 1 ,15436   ,134.6,136.3,137.1
XS GIS Cut Line= 2
1658626.77145803522232.7144356081658348.31143273521908.825886542
#Sta/Elev= 30
       0 1059.25     7.5 1057.47    23.8 1050.63    53.9 1036.49      74 1025.83
    84.1 1019.25    91.2 1011.39    97.4 1006.95     132  990.28   156.4  969.87
   172.7  958.55   177.3  956.99   186.6  956.54   198.3  954.37  206.49951.7021
   219.2  951.19   227.2  951.71   237.8  953.39   248.8  960.06   260.2  965.36
   274.8  973.54   300.6  989.74   310.5  994.78   330.9 1003.19   340.2 1009.23
   354.1 1020.15   375.1 1032.35   406.1 1056.57   416.9 1062.38   427.1 1064.84
#Mann= 3 ,-1,0
       0      .1       0  206.49    .045       0   227.2      .1       0
Bank Sta=206.49,227.2
XS Rating Curve= 0 ,0
Exp/Cntr(USF)=0,0
Exp/Cntr=0.3,0.1

Type RM Length L Ch R = 1 ,15300   ,302.1,298.1,291.8
XS GIS Cut Line= 6
1658704.25004467522168.545199335 1658658.6510545522093.754994586
1658618.87193459522030.1183108391658562.90583917 521947.24610126
1658523.53583917 521883.333827511658481.74786501521806.182078928
#Sta/Elev= 30
       0 1056.66    15.2 1050.53    57.5 1029.14    79.4 1017.87    95.9 1007.74
   108.8 1002.17   127.1   995.5     154  977.98   170.2  968.01     182  959.02
   186.4  957.11   193.4  955.45   200.6  950.56  203.52949.7215   213.2  948.54
   228.7949.7213     236  951.58   245.5  952.59   252.8  956.23   282.9  979.48
   290.6  985.83   295.4  990.47   300.2  993.87   325.5 1007.17   341.5 1019.53
   360.4 1030.09   379.5  1042.7   401.2 1058.97   412.4 1064.05   425.4 1068.37
#Mann= 3 ,-1,0
       0      .1       0  203.52    .045       0   228.7      .1       0
Bank Sta=203.52,228.7
XS Rating Curve= 0 ,0
Exp/Cntr(USF)=0,0
Exp/Cntr=0.3,0.1

Type RM Length L Ch R = 1 ,15002   ,167.9,174.9,182
XS GIS Cut Line= 6
1658937.02156076521962.6102437531658898.97931401521865.614374757
1658843.02174875521812.6679583341658758.44186543521759.179876342
1658693.56371434521721.5513426661658617.87324892521677.650511846
#Sta/Elev= 30
       0 1053.52    28.8 1039.93    46.5 1030.48    67.6 1014.72    88.8 1000.93
   102.4  987.84   123.4  971.52   145.3  956.01   158.3  947.93   161.4  946.72
     166  946.13   190.3  946.92   210.8  946.82  219.84944.8088   233.8  944.18
   241.9  944.31  243.85944.8104   245.7  945.54   251.7  949.76   264.7  954.44
   276.3  960.57   287.3  968.58   307.2  985.64   319.7  995.24   348.6 1008.88
   367.9 1021.51   394.5 1035.99   428.6 1059.43   436.2 1063.48   443.8 1066.46
#Mann= 3 ,-1,0
       0      .1       0  219.84    .045       0  243.85      .1       0
Bank Sta=219.84,243.85
XS Rating Curve= 0 ,0
Exp/Cntr(USF)=0,0
Exp/Cntr=0.3,0.1

Type RM Length L Ch R = 1 ,14827   ,230.3,245.2,256.6
XS GIS Cut Line= 4
 1658994.4468172521943.9136670061658963.04130211521729.489805379
1658900.15887562521589.6691079091658771.11870991521502.792524062
#Sta/Elev= 30
       0 1054.81    18.2  1047.9    38.4 1037.89    77.9 1011.21   110.7  994.86
   137.6  973.19   159.8  951.93   164.1  949.37     174  947.45   180.7  944.62
   187.3  943.34   217.2  944.29     228  946.31   231.6  945.35  235.58942.6323
   238.8  941.81   249.6  941.59  260.97942.6298   267.5  944.99   299.9  947.31
   306.3  948.61   332.3  964.61   350.3  977.67   363.9  985.53   389.9  996.55
   404.4 1000.82   449.3 1016.87   480.9 1030.47   508.1    1040   525.6 1044.68
#Mann= 3 ,-1,0
       0      .1       0  235.58    .045       0  260.97      .1       0
Bank Sta=235.58,260.97
XS Rating Curve= 0 ,0
Exp/Cntr(USF)=0,0
Exp/Cntr=0.3,0.1

Type RM Length L Ch R = 1 ,14582   ,180.2,181.6,182.2
XS GIS Cut Line= 2
1659021.63794209521955.4491355491659345.77332619521514.444317706
#Sta/Elev= 30
       0 1056.77    32.6 1041.33    44.8 1034.44    60.6 1024.08    77.4 1010.68
   101.8  995.31   128.9  969.88   147.7  956.02   168.8  943.38     190  938.57
     197  937.66   211.7  937.57   225.2  938.59   232.1  939.33   236.9  940.77
   248.6  940.63   256.5  942.61   265.6  942.34   281.5  954.03   321.7  971.69
   347.2  985.04   358.3  990.17   390.9 1000.54   411.2 1008.11   442.8 1023.28
   466.9 1032.35   500.8 1049.53   529.3  1061.7   534.9 1063.39   547.3 1065.13
#Mann= 3 ,-1,0
       0      .1       0     190    .045       0   225.2      .1       0
Bank Sta=190,225.2
XS Rating Curve= 0 ,0
Exp/Cntr(USF)=0,0
Exp/Cntr=0.3,0.1

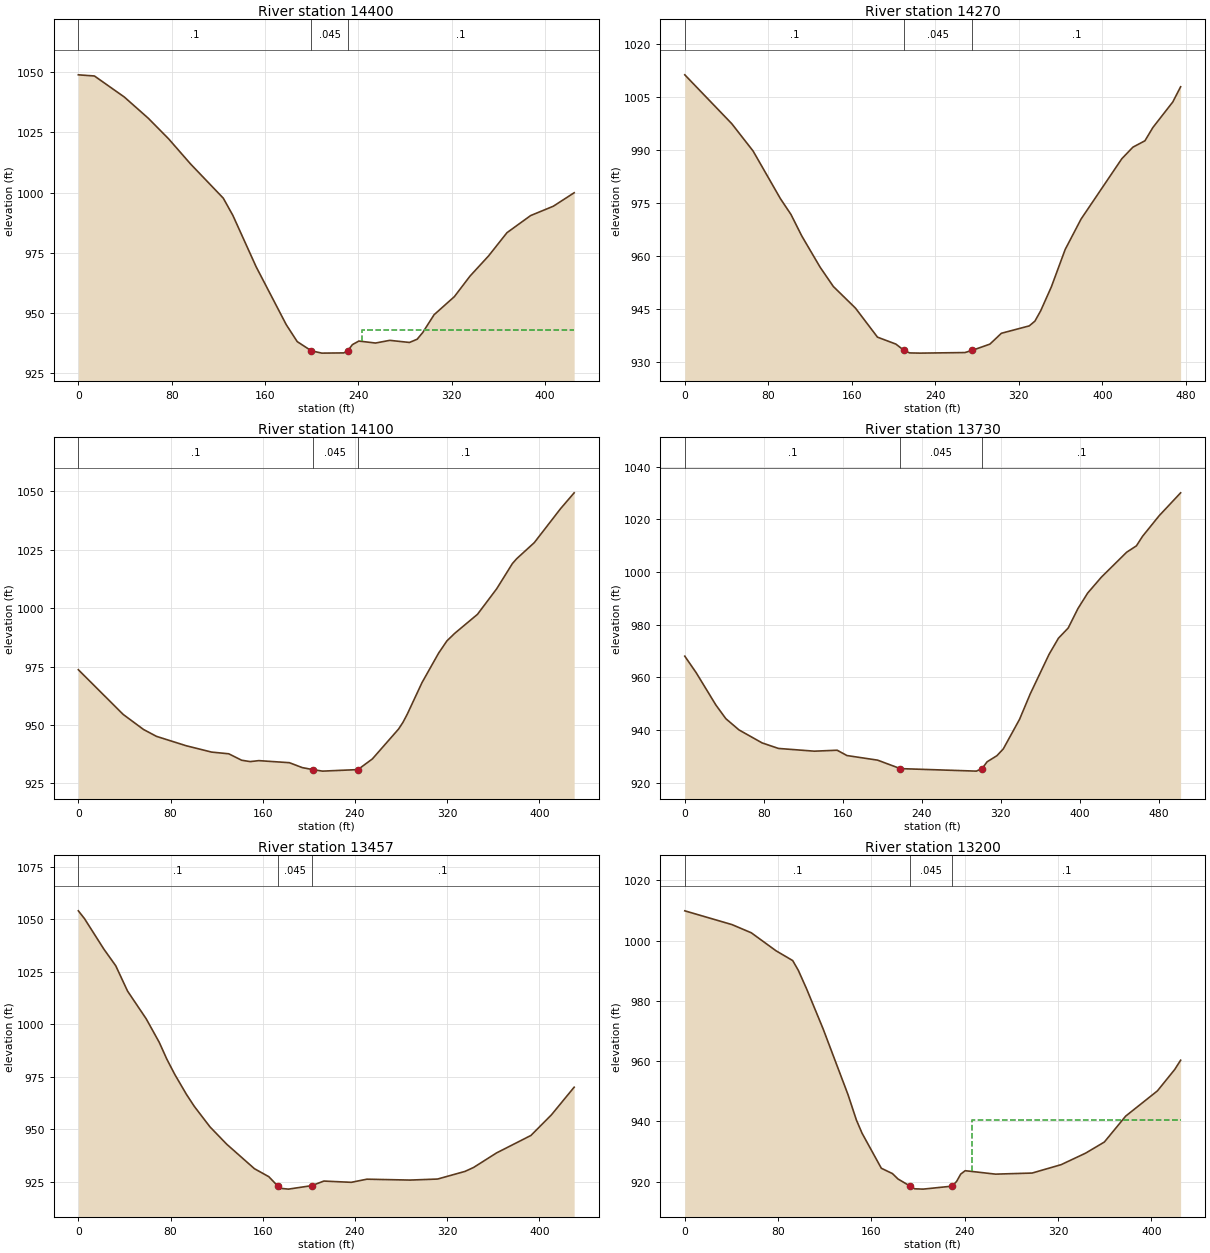
Type RM Length L Ch R = 1 ,14400   ,151.8,129.9,106.3
XS GIS Cut Line= 6
1659152.74521068522079.6900620911659203.60009584522008.503852755
1659247.19613726521947.4793685081659306.86957434521867.234450251
1659350.77926342521806.4169865851659400.00357443 521733.89810276
#Sta/Elev= 30
       0 1048.86    13.8 1048.38    39.4 1039.66      60 1030.83    77.3 1022.35
    96.2 1011.88   124.3  997.66   132.5  990.52   152.5  969.15   178.3  945.15
   187.7  938.13  199.84 934.316   208.8  933.37   227.6  933.46  230.88934.3159
     235   936.9   240.5  938.38   254.8  937.56     267  938.67   283.9   937.8
   290.5  939.14   295.3  941.93     305   949.3   322.4  956.81   335.8  965.33
   351.7   973.7   367.5  983.35   387.8  990.46   407.2  994.32   425.1  999.92
#Mann= 3 ,-1,0
       0      .1       0  199.84    .045       0  230.88      .1       0
#XS Ineff= 2 , 0
                          243.32          943.07
Permanent Ineff=
       F       F
Bank Sta=199.84,230.88
XS Rating Curve= 0 ,0
Exp/Cntr(USF)=0,0
Exp/Cntr=0.3,0.1

Type RM Length L Ch R = 1 ,14270   ,141,170.3,202.5
XS GIS Cut Line= 4
1659235.85049023 522150.89901082 1659387.8965012522027.117963426
1659376.20065421 521931.601879611659533.11993476521838.035103627
#Sta/Elev= 30
       0  1011.2      45  997.37    65.4  989.65    91.6  976.16   101.7  971.69
   112.1  965.58   129.6  956.78   142.3   951.3   163.5  945.18   184.6  936.96
   202.2     935  210.02933.2263   215.4   932.5   225.3  932.44   268.3   932.6
  275.37933.2269   292.3  934.99   303.3  938.06     330  940.15   335.4  941.49
   340.9   944.4   351.2  951.22   364.4  961.77   379.6  970.37   418.7  987.47
   429.3  990.73   440.8  992.53   448.4  996.28   467.5 1003.52     475 1007.82
#Mann= 3 ,-1,0
       0      .1       0  210.02    .045       0  275.37      .1       0
Bank Sta=210.02,275.37
XS Rating Curve= 0 ,0
Exp/Cntr(USF)=0,0
Exp/Cntr=0.3,0.1

Type RM Length L Ch R = 1 ,14100   ,316.3,369.6,417.9
XS GIS Cut Line= 6
1659297.86499918522211.9640757591659381.19029184522173.182657257
1659447.88208759522137.2086478321659534.26052375522086.822921842
1659599.04451492522049.0332992521659674.62572859522004.945789009
#Sta/Elev= 30
       0  973.69    38.9  954.56    56.6   948.1    67.8  945.17    93.6  941.15
   115.6  938.44   130.5  937.71   141.7  934.95   149.1  934.37   156.6  934.78
   183.1   933.9   194.3   931.8   203.3930.9467   211.9  930.29  242.58930.9464
   255.1   935.5   277.9  948.32   281.7  951.19   285.5  954.77   298.2  968.18
   312.6  980.79   319.8  986.02   326.6  989.26   346.3  997.38     363 1008.33
   376.6  1019.1   380.4 1021.22   395.6 1028.06   418.4  1042.6   430.2 1049.38
#Mann= 3 ,-1,0
       0      .1       0   203.3    .045       0  242.58      .1       0
Bank Sta=203.3,242.58
XS Rating Curve= 0 ,0
Exp/Cntr(USF)=0,0
Exp/Cntr=0.3,0.1

Type RM Length L Ch R = 1 ,13730   ,318.2,273.4,230
XS GIS Cut Line= 5
1659282.45033184 522365.038244681659368.37601301522381.562161759
1659460.43658579522392.4766728671659491.49435143522508.826869271
1659692.74647918522522.710749332
#Sta/Elev= 30
       0  968.07    11.5  961.81    31.5  949.52    41.6  944.32    54.9  940.06
    78.3  935.13    94.9  933.02   131.3  931.98   154.4  932.34   164.3  930.32
   195.4  928.57  218.35925.3541   295.4   924.4  301.18925.3517   306.3  927.94
   316.2  930.25   322.7  932.83   339.2  944.09     350  953.73   369.1  968.78
   378.6  974.89   388.5  978.78   398.4  986.18   408.2  992.04   422.1  998.09
   447.7 1007.56   457.6 1009.99   463.8  1013.6   480.6 1021.41   502.4 1030.13
#Mann= 3 ,-1,0
       0      .1       0  218.35    .045       0  301.18      .1       0
Bank Sta=218.35,301.18
XS Rating Curve= 0 ,0
Exp/Cntr(USF)=0,0
Exp/Cntr=0.3,0.1

Type RM Length L Ch R = 1 ,13457   ,257.7,257.4,250.1
XS GIS Cut Line= 2
1659239.46400627522784.8263437151659654.02055764 522669.74741321
#Sta/Elev= 30
       0 1054.08     5.3  1050.4    22.2 1035.81    32.5 1027.89    42.7 1015.87
    58.9 1002.66    70.2  991.47    76.8  983.45    83.6  976.27    93.8  966.69
   100.6  960.99   114.2  951.23   128.8  942.93   152.8   931.3   165.3  927.48
  172.82  923.17   175.5  921.94   182.3  921.57   202.7  923.25     213  925.41
   236.8  924.81   250.4   926.3   287.9  925.88   311.7  926.37   335.5  930.01
   342.9  931.87   362.8  938.79   392.7  947.13   410.4  956.89   430.2   970.1
#Mann= 3 ,-1,0
       0      .1       0  172.82    .045       0   202.7      .1       0
Bank Sta=172.82,202.7
XS Rating Curve= 0 ,0
Exp/Cntr(USF)=0,0
Exp/Cntr=0.3,0.1

Type RM Length L Ch R = 1 ,13200   ,301.5,305,293.5
XS GIS Cut Line= 6
1659389.59808342523052.0995345861659462.80036484523004.008423418
1659525.78645934522963.1932163391659611.30531718 522911.35506542
1659675.75269485 522872.994577841659750.94053659522828.239089921
#Sta/Elev= 30
       0 1009.84    40.4 1005.28      57 1002.56    78.3  996.57    92.5  993.35
    97.3  990.13   104.4  983.99   118.6  970.69     140  948.82   147.1   940.5
     152  936.08   168.5  924.48     178  922.72   182.8  920.92  193.22918.5487
   197.1  917.67   204.3  917.56  229.19 918.549     233   920.1   236.6  922.56
   240.4  923.67   266.4  922.53   297.8  922.89   322.7  925.68   343.6  929.48
   359.7  933.17     378  941.77   405.2  950.14     420  957.21   425.1   960.3
#Mann= 3 ,-1,0
       0      .1       0  193.22    .045       0  229.19      .1       0
#XS Ineff= 2 , 0
                          246.18          940.51
Permanent Ineff=
       F       F
Bank Sta=193.22,229.19
XS Rating Curve= 0 ,0
Exp/Cntr(USF)=0,0
Exp/Cntr=0.3,0.1

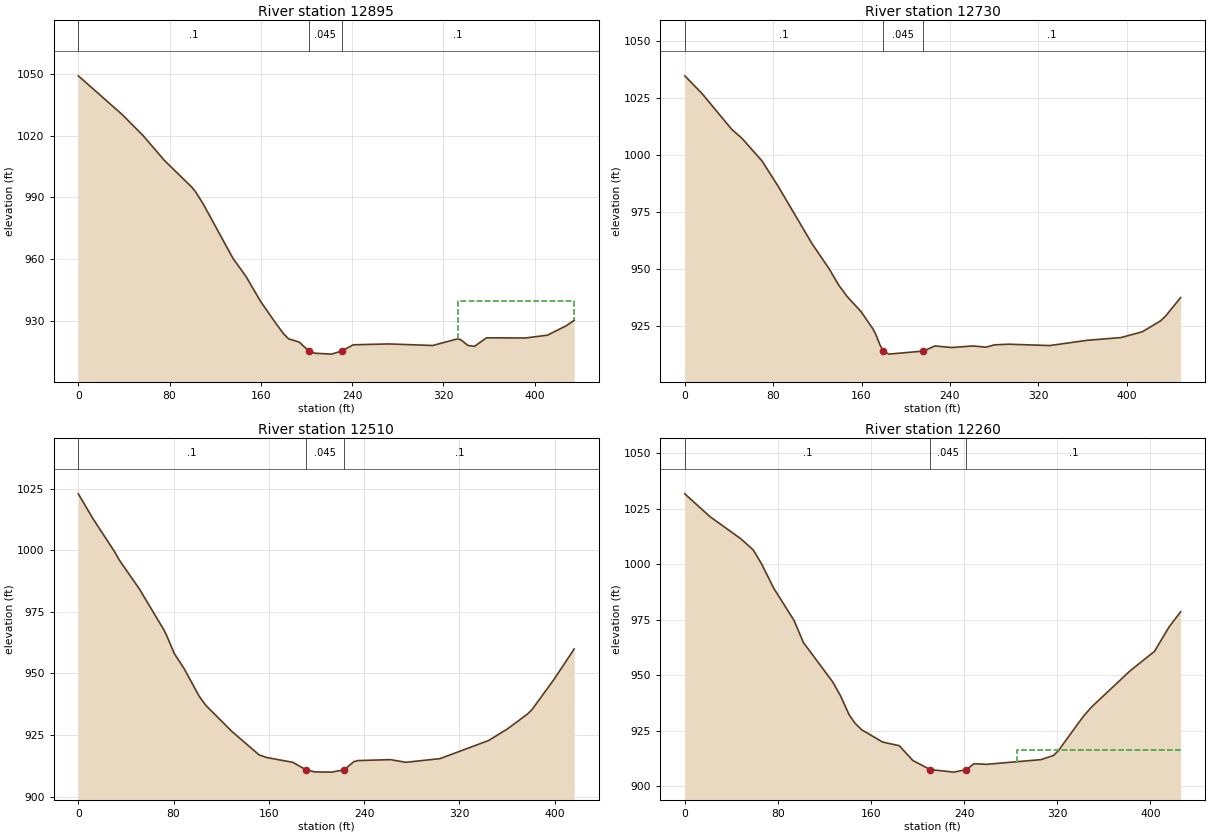
Type RM Length L Ch R = 1 ,12895   ,164.4,165,155.2
XS GIS Cut Line= 6
1659558.86250867523350.3571401691659621.79545367523287.156807259
1659671.77730909523228.9380916661659741.38773417523155.698080674
1659805.24981117 523115.377623261659873.30118425 523053.16711776
#Sta/Elev= 30
       0 1049.13    38.1 1030.47    56.7  1020.1    75.3 1008.06    99.3  995.05
     103  992.54   109.4  986.87   135.5  960.38   147.2  951.33   159.7  939.43
   172.7  929.07   179.7  923.75   184.3  921.13   193.6  919.59  202.08915.2307
   207.7  914.12     222   913.7  230.95915.2271     241  918.24   272.1  918.66
   310.7   917.9   332.1  921.08   335.1   920.8   341.6  917.93   347.3  917.49
   357.9  921.64   391.8  921.55   411.3  922.92   427.6  927.46   434.7  930.11
#Mann= 3 ,-1,0
       0      .1       0  202.08    .045       0  230.95      .1       0
#XS Ineff= 2 , 0
                          333.24          939.39
Permanent Ineff=
       F       F
Bank Sta=202.08,230.95
XS Rating Curve= 0 ,0
Exp/Cntr(USF)=0,0
Exp/Cntr=0.3,0.1

Type RM Length L Ch R = 1 ,12730   ,206.8,219.1,200
XS GIS Cut Line= 2
1659710.03252179523478.1415064221659941.78356416523093.694683803
#Sta/Elev= 30
       0 1034.63    15.8 1026.75    42.6 1011.09    51.6  1007.3    69.9   997.3
    84.2  986.43   115.3  960.91   130.7  949.98   139.2  942.93   146.9  937.86
   159.6  931.17   170.3  923.64   172.9  921.28   176.7  916.54  179.79913.8891
   184.6  912.54   216.1913.8922   226.5  916.13   241.8  915.44     261  916.13
   272.5  915.59   280.3   916.6     293  916.89   330.4   916.3   364.4  918.61
   394.9  919.81   414.2  922.34   430.8  927.16   435.6  929.39   448.9  937.36
#Mann= 3 ,-1,0
       0      .1       0  179.79    .045       0   216.1      .1       0
Bank Sta=179.79,216.1
XS Rating Curve= 0 ,0
Exp/Cntr(USF)=0,0
Exp/Cntr=0.3,0.1

Type RM Length L Ch R = 1 ,12510   ,248.9,250,247.7
XS GIS Cut Line= 2
1659888.84905343523531.2750854191660072.19630498523157.248982184
#Sta/Elev= 30
       0 1022.92    12.1 1012.99    30.4  999.47    34.4  996.06    51.3  984.29
    71.6  967.92    74.2  965.42    80.7  958.02    88.9  951.97   101.4  940.87
   107.1  937.07   129.1  926.45   151.8  916.98   158.3   915.9   180.2  913.94
  191.12 910.944   198.5  910.06   212.9  909.97  223.47910.9444   231.4  914.22
     235  914.66   262.2  915.04   275.2  913.96   303.9  915.46   344.6  922.79
   360.3  927.45   377.5  933.61   381.2   935.4   399.5  947.56   416.5  959.94
#Mann= 3 ,-1,0
       0      .1       0  191.12    .045       0  223.47      .1       0
Bank Sta=191.12,223.47
XS Rating Curve= 0 ,0
Exp/Cntr(USF)=0,0
Exp/Cntr=0.3,0.1

Type RM Length L Ch R = 1 ,12260   ,225.3,226.3,228.1
XS GIS Cut Line= 6
1660106.34914631523669.3984227341660141.58824906523589.308359818
1660171.79324115523520.659546987 1660211.6307599523428.936305241
 1660242.1818799523360.3098020711660283.15686356523281.859499649
#Sta/Elev= 30
       0 1031.66    21.7 1021.36    48.1 1011.43    58.9 1006.33      66 1000.07
    76.5  989.05    93.9  974.59   101.9  964.68     127  946.98   133.8  940.68
   141.2  932.13   146.2  928.35     152  925.34     170   919.8   184.3  918.16
     196  911.49  210.87907.4036   231.4  906.25  242.05907.4054   248.6  910.04
   259.4  909.77   306.1  911.88   316.8  913.75   320.8  915.74   342.1  931.11
   349.5  935.57   382.8  951.96   403.6  960.64   416.1  971.61   426.1  978.49
#Mann= 3 ,-1,0
       0      .1       0  210.87    .045       0  242.05      .1       0
#XS Ineff= 2 , 0
                           285.2          916.42
Permanent Ineff=
       F       F
Bank Sta=210.87,242.05
XS Rating Curve= 0 ,0
Exp/Cntr(USF)=0,0
Exp/Cntr=0.3,0.1