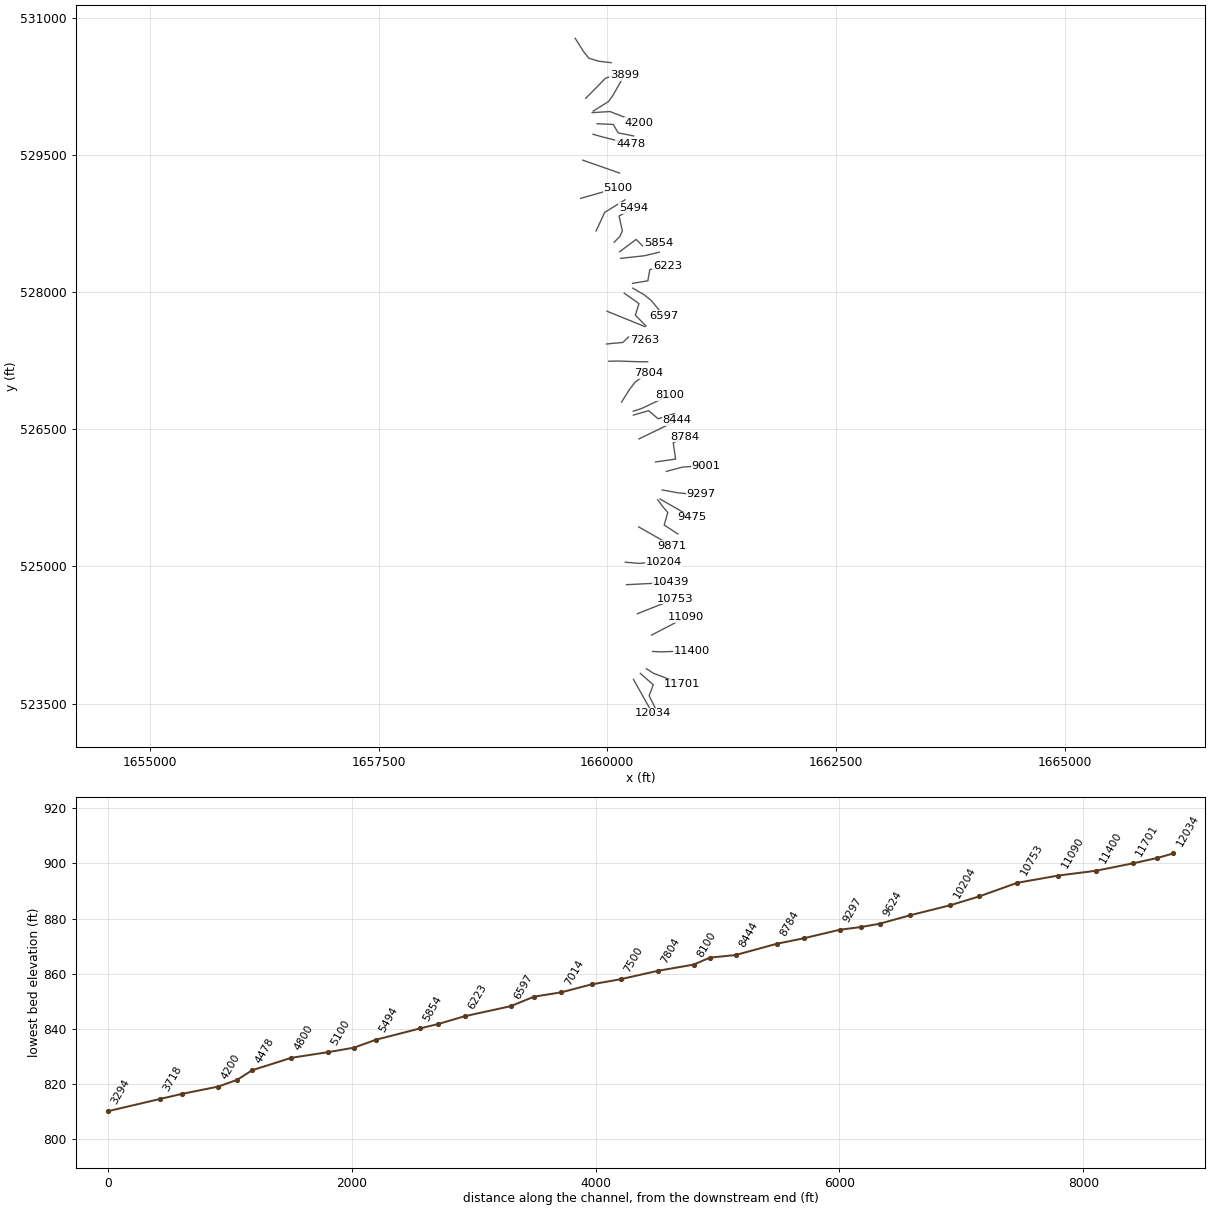
HEC-RAS study StullRn.prj: StullRn

--- StullRn.g01 (geometry) --- (continued)

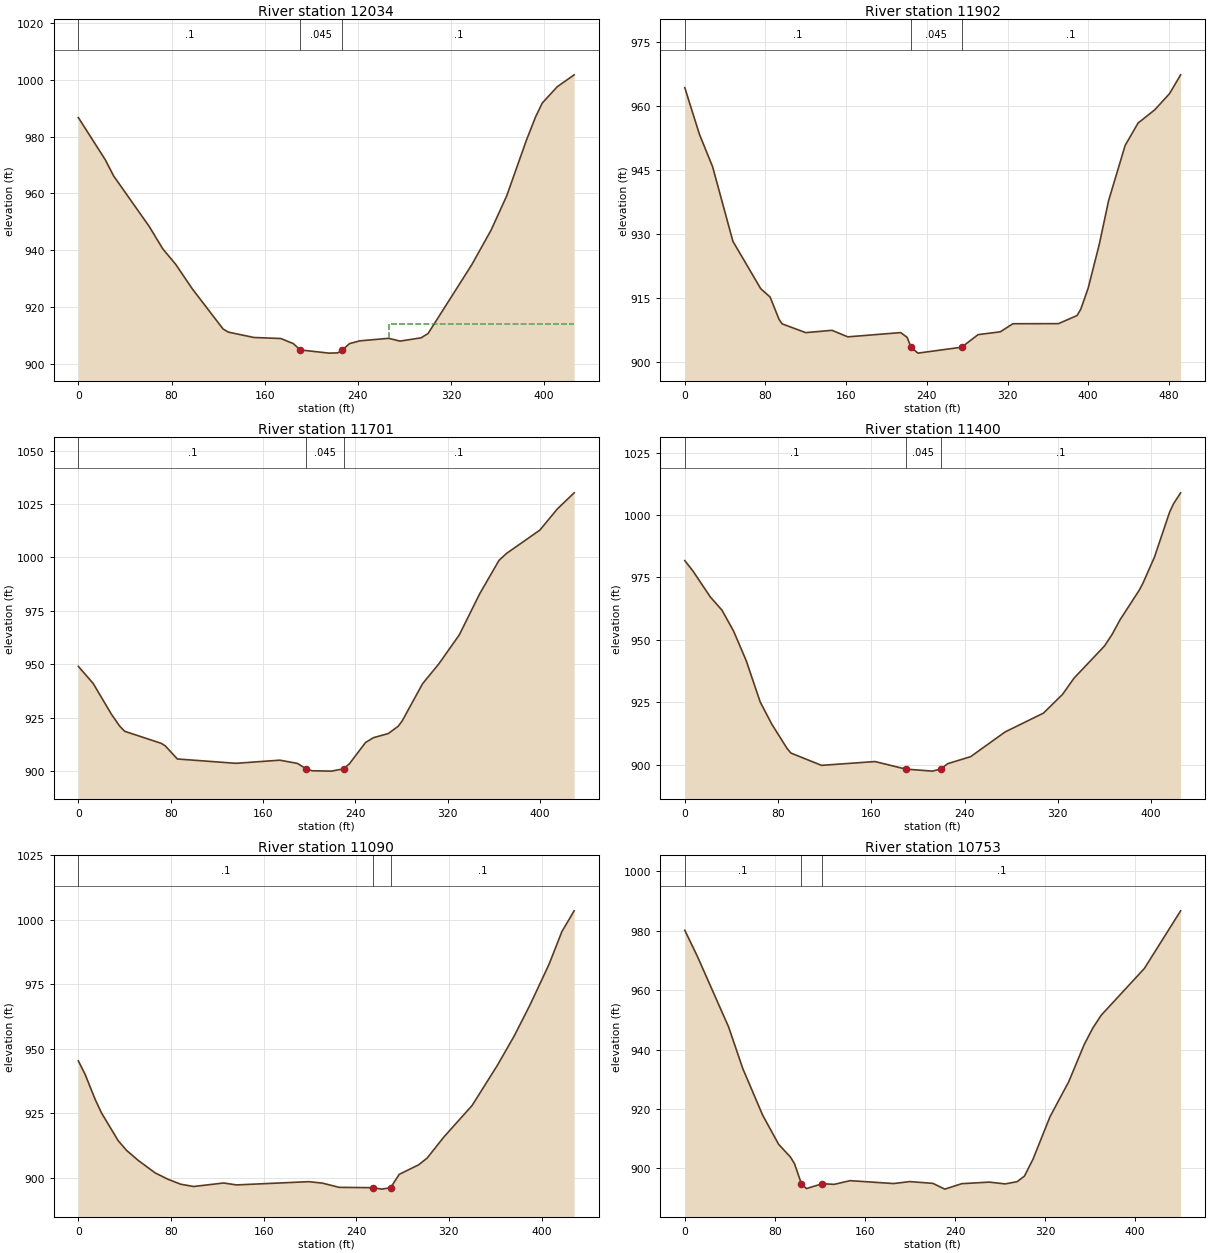
Type RM Length L Ch R = 1 ,12034   ,134.4,132.3,95.2
XS GIS Cut Line= 2
1660286.83733729 523764.020535211660494.76350615523392.569098147
#Sta/Elev= 30
       0  986.78    23.1  971.93    30.3  966.19    61.1  948.22    72.4  940.51
    83.7  934.94    97.8  926.37   124.3  912.17   128.8  911.07   150.8  909.18
   173.9  908.81   184.6  907.01  190.47 904.793   215.3  903.66   222.8  903.75
  226.72904.7909   232.8  907.01   241.6  907.99   266.5  908.89   276.2   907.9
   294.3  909.06   300.3  910.59   337.9  934.92   354.4  947.08   367.8  959.15
   384.5  978.55   392.5  986.95   398.3  991.89   411.1  997.63   425.7 1001.86
#Mann= 3 ,-1,0
       0      .1       0  190.47    .045       0  226.72      .1       0
#XS Ineff= 2 , 0
                          267.15          914.08
Permanent Ineff=
       F       F
Bank Sta=190.47,226.72
XS Rating Curve= 0 ,0
Exp/Cntr(USF)=0,0
Exp/Cntr=0.3,0.1

Type RM Length L Ch R = 1 ,11902   ,183.8,201.2,245.2
XS GIS Cut Line= 4
1660362.28999365523829.5218151511660503.21050676523704.674941183
1660457.40177268523585.7671633711660536.40712876 523428.65430085
#Sta/Elev= 30
       0  964.29    14.5  953.37    27.6  945.72    47.7  928.24    75.3  917.12
    84.6  915.16    93.4  909.95    96.5  908.87   119.9  906.81     146  907.35
   161.6  905.82   214.1  906.82   220.5  905.68  224.25903.3911   231.1     902
   274.5903.3915   290.8  906.34   312.8     907   325.3   908.9   370.5  908.92
   388.9  910.82   392.6   912.3   399.9  917.23   410.9  927.48   420.2  937.79
   436.6  950.74   449.4  955.99     466  959.11   480.7  962.93   491.6  967.31
#Mann= 3 ,-1,0
       0      .1       0  224.25    .045       0   274.5      .1       0
Bank Sta=224.25,274.5
XS Rating Curve= 0 ,0
Exp/Cntr(USF)=0,0
Exp/Cntr=0.3,0.1

Type RM Length L Ch R = 1 ,11701   ,290,300.6,302.8
XS GIS Cut Line= 6
1660427.87094125523880.6739929171660504.99906784523831.197713926
1660575.61933343523804.8995381741660668.96822809523768.949806929
1660738.60424368523741.0958600041660819.84620717523708.599533916
#Sta/Elev= 30
       0  949.05    12.9  941.04    28.5  926.79    35.9  921.03    40.2  918.67
    71.8  913.04    75.3  911.87    85.8  905.72   136.5  903.69   174.6  905.16
   189.8  903.65  197.46901.1137   202.5  900.21   219.2  900.04  229.79901.1148
   234.8  903.46   248.8  913.44   255.7  915.69   268.5  917.62     277  920.99
   280.5  923.49   298.2  940.94   312.3  950.21     330  963.77   347.7  983.02
   364.4  998.61   370.9 1001.87   399.8 1012.78   414.8 1022.61   429.5 1030.22
#Mann= 3 ,-1,0
       0      .1       0  197.46    .045       0  229.79      .1       0
Bank Sta=197.46,229.79
XS Rating Curve= 0 ,0
Exp/Cntr(USF)=0,0
Exp/Cntr=0.3,0.1

Type RM Length L Ch R = 1 ,11400   ,305.9,309.7,312.5
XS GIS Cut Line= 6
1660495.46299767524069.740872011 1660583.2456305524065.533531338
1660658.20315775524068.0604291711660758.14652742524071.430173084
 1660833.1037266524073.956414759  1660920.554011524076.906868175
#Sta/Elev= 30
       0  981.73     6.8  977.71      22  967.12    31.9  961.89    41.8  953.55
    52.7  941.66    64.7  925.09    74.6  916.24    87.7   906.5      91  904.64
   117.3  899.69   163.2  901.22   189.5   898.2   212.5  897.38  219.43   898.2
   225.6  900.37   245.3  903.19   274.8  913.08   307.7  920.62   324.1  928.14
   333.9  934.62   360.1  947.54   366.8  952.31   373.3  957.94   389.7  969.74
     393  972.62   402.9  983.09     416 1001.23   419.3 1004.51   425.4 1008.91
#Mann= 3 ,-1,0
       0      .1       0   189.5    .045       0  219.43      .1       0
Bank Sta=189.5,219.43
XS Rating Curve= 0 ,0
Exp/Cntr(USF)=0,0
Exp/Cntr=0.3,0.1

Type RM Length L Ch R = 1 ,11090   ,337,337.5,332.4
XS GIS Cut Line= 2
1660484.84720525524249.2743055821660864.79053656524446.727351074
#Sta/Elev= 30
       0  945.33     5.9  940.06    14.6  930.33    20.1  925.09    34.4  914.42
    41.5  910.71    51.6   906.8    66.4  901.91    77.3  899.48    88.5  897.52
    99.6  896.65   125.5  898.01   136.6  897.26     199  898.52   210.6  897.97
   225.3  896.32  254.51896.1843   262.2  895.63   269.7  896.19   277.1  901.35
   293.9  905.05   301.2  907.64   315.7  915.84   340.1  928.06     362  943.68
   376.6  955.12   390.1  967.03   406.5  982.73   417.6  995.42   428.2 1003.47
#Mann= 3 ,-1,0
       0      .1       0  254.51    .045       0   269.7      .1       0
Bank Sta=254.51,269.7
XS Rating Curve= 0 ,0
Exp/Cntr(USF)=0,0
Exp/Cntr=0.3,0.1

Type RM Length L Ch R = 1 ,10753   ,316.2,313.4,306.7
XS GIS Cut Line= 2
1660328.56651095524482.3098074721660737.77045472524644.969577698
#Sta/Elev= 30
       0  980.15    11.1  971.43    38.9  947.61    51.5  933.59    69.1  917.93
    83.3   908.1    93.8   903.8    97.4  901.56  103.63  894.76     108  893.18
   122.1   894.8   132.7   894.6   146.8  895.84   185.4  894.87   199.8  895.53
   220.3  894.93   230.9  892.99     246  894.83   270.4  895.35   284.5  894.75
   295.1   895.5   301.6  897.37   309.2  903.06   324.3  917.36     341  929.21
   354.6  941.61   362.2  947.15   369.8  951.56   408.1  967.29   440.3   986.7
#Mann= 3 ,-1,0
       0      .1       0  103.63    .045       0   122.1      .1       0
Bank Sta=103.63,122.1
XS Rating Curve= 0 ,0
Exp/Cntr(USF)=0,0
Exp/Cntr=0.3,0.1

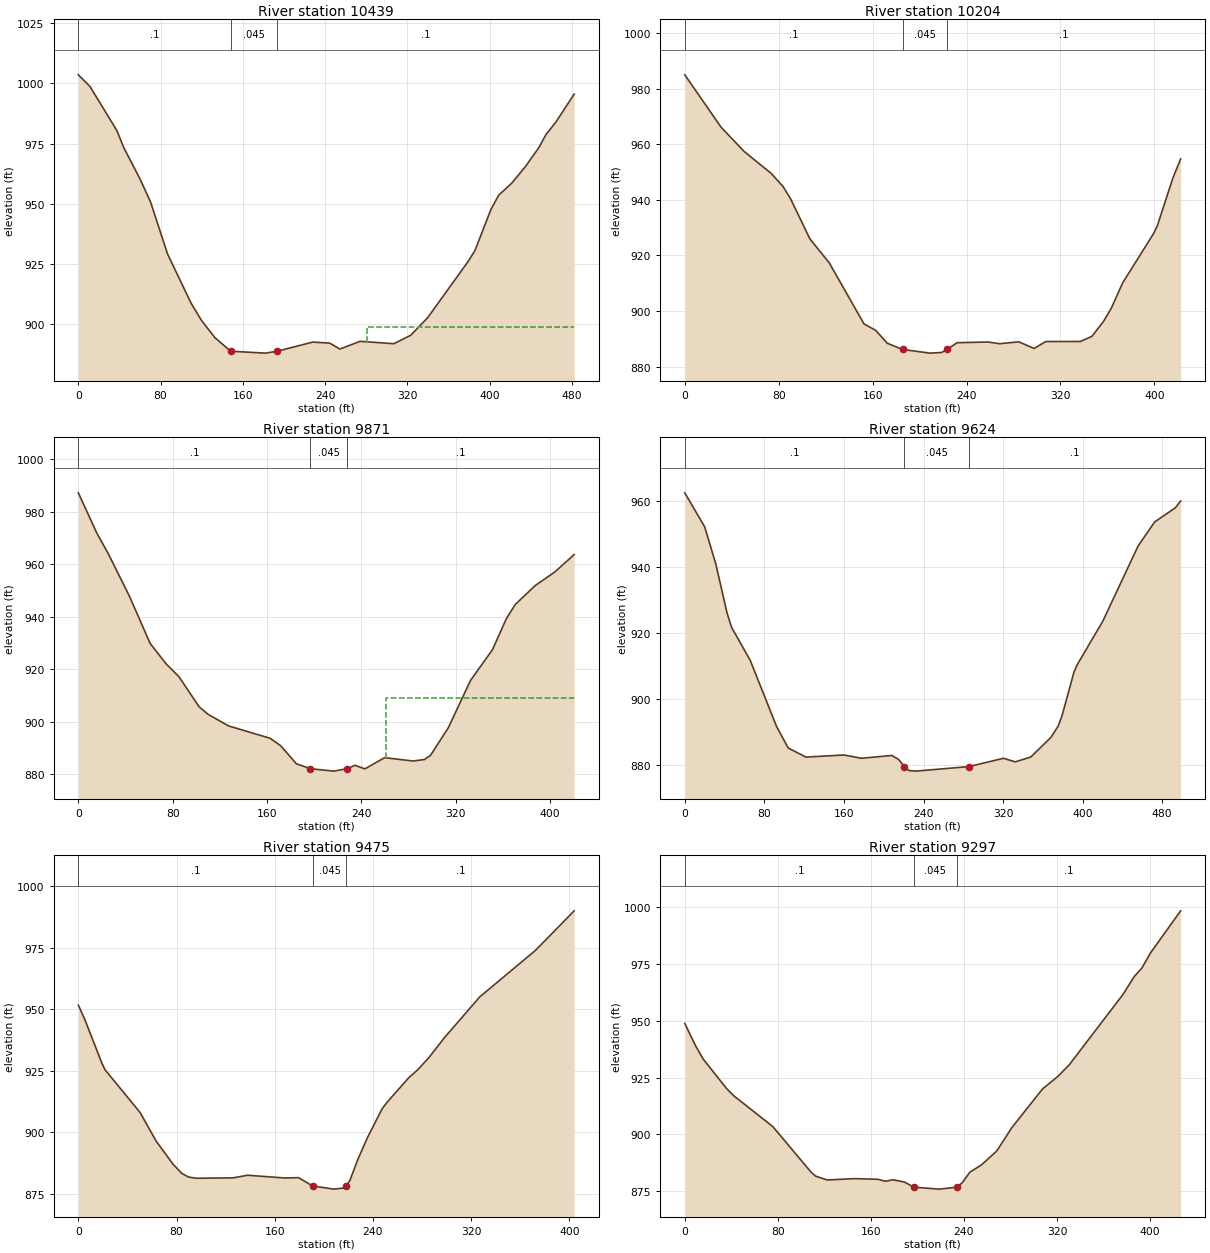
Type RM Length L Ch R = 1 ,10439   ,232.4,235.3,234
XS GIS Cut Line= 2
 1660210.9534905524800.3106050941660692.68270809524824.625103651
#Sta/Elev= 30
       0 1003.57    11.3  998.75    37.5  980.43    44.1  973.45    60.5  959.91
    70.4  950.61    86.8  929.18   109.8  908.66   119.7  901.67   132.8  894.49
  148.18888.8163   182.1  888.03  193.36888.8151   228.1  892.62   244.5  892.18
   254.4  889.72   274.1  892.93   306.9  891.94   323.3  895.43   339.8  902.74
   379.2  926.11   385.8   930.6   401.2  947.54   408.8  953.56   421.9  958.73
     435  965.54   448.2  973.53   454.7  978.65   464.6  983.99   482.3  995.57
#Mann= 3 ,-1,0
       0      .1       0  148.18    .045       0  193.36      .1       0
#XS Ineff= 2 , 0
                          281.23          898.97
Permanent Ineff=
       F       F
Bank Sta=148.18,193.36
XS Rating Curve= 0 ,0
Exp/Cntr(USF)=0,0
Exp/Cntr=0.3,0.1

Type RM Length L Ch R = 1 ,10204   ,340.4,332.7,319
XS GIS Cut Line= 5
1660198.00006657525046.3999677991660352.90422767525033.017160669
1660453.77968208525043.4505387541660530.55708759525044.305852011
1660619.24424617525044.869499177
#Sta/Elev= 30
       0  984.99    30.9  966.15    50.6   957.4    73.7  949.49    83.6  944.86
    90.2  940.33   106.6  925.94   123.1  917.32   152.7  895.36   162.6  893.07
   172.5  888.41  185.47886.1957   208.8  884.86   218.7  885.09  223.66 886.194
   231.9  888.61   258.3  888.86   268.1  888.24   284.5  888.93   297.6  886.54
   307.5  889.03     337  889.06   346.8  890.89   356.7  896.27   363.3  900.97
   373.1   910.2   399.3  927.82   402.6  930.73   415.7  947.72   422.4  954.74
#Mann= 3 ,-1,0
       0      .1       0  185.47    .045       0  223.66      .1       0
Bank Sta=185.47,223.66
XS Rating Curve= 0 ,0
Exp/Cntr(USF)=0,0
Exp/Cntr=0.3,0.1

Type RM Length L Ch R = 1 ,9871    ,257.2,247.8,191.1
XS GIS Cut Line= 2
1660343.15129443525432.6551409211660708.61170822525224.764945573
#Sta/Elev= 30
       0  987.22    15.6  971.96    25.7  963.75    43.3  947.87    60.9  929.84
    74.6  921.99    85.4  917.12   102.4  905.71     110  902.83   127.5  898.39
   162.8  893.68   171.6  890.85   184.9  883.99   196.8   882.1   216.5  881.18
  228.26882.1163   234.5  883.42     243  882.04   259.8  886.32   283.9  885.03
   293.5  885.61   298.7  887.19   313.8  897.73   332.7   915.8   351.3  927.51
   362.9   939.2   370.5  944.66   387.5   951.9   404.4  957.17   420.5   963.7
#Mann= 3 ,-1,0
       0      .1       0   196.8    .045       0  228.26      .1       0
#XS Ineff= 2 , 0
                          260.88          909.09
Permanent Ineff=
       F       F
Bank Sta=196.8,228.26
XS Rating Curve= 0 ,0
Exp/Cntr(USF)=0,0
Exp/Cntr=0.3,0.1

Type RM Length L Ch R = 1 ,9624    ,133.9,148.9,198.8
XS GIS Cut Line= 5
1660551.67318709525729.7221320871660603.15110251525658.646486834
1660661.87026864 525589.867198661660622.44920843525453.227407549
1660771.34195035525355.502236264
#Sta/Elev= 30
       0  962.62      20  952.29    31.2  941.01    42.4  926.24      47   921.8
    65.8  911.76    92.2  891.75   103.9  885.17   121.8   882.4     160  883.04
   177.7  882.04   208.2   882.9     215  881.67  220.88879.5071   225.3  878.33
   232.1  878.14  285.38879.5083   320.4  882.04   332.2  880.95   347.9  882.43
   368.1  888.39   375.4  891.81   379.3  894.99   391.1  908.01   394.2  910.26
   420.3  923.68   455.8  946.51   472.4  953.78   493.1  958.05   498.5  960.15
#Mann= 3 ,-1,0
       0      .1       0  220.88    .045       0  285.38      .1       0
Bank Sta=220.88,285.38
XS Rating Curve= 0 ,0
Exp/Cntr(USF)=0,0
Exp/Cntr=0.3,0.1

Type RM Length L Ch R = 1 ,9475    ,170,178.1,183.6
XS GIS Cut Line= 2
1660578.52906023 525737.047884931660928.53849116525535.558776323
#Sta/Elev= 30
       0   951.6     4.9  946.28    19.3  927.95    21.7  925.44    50.3  908.06
    63.4  896.46      77  887.19    84.2  883.37    89.7  881.87    96.2  881.37
   126.4  881.56   137.8  882.61   168.1  881.49   179.4  881.62   190.8  878.28
   208.1  876.97   216.3  877.43  218.37878.2691   221.3  880.59   227.8  889.16
   235.5  897.83   247.5  909.59   251.3  912.09   269.2  922.18   276.4  925.35
   285.4  930.23     298  938.27     327  954.97   372.4  973.84   403.9  989.88
#Mann= 3 ,-1,0
       0      .1       0   190.8    .045       0  218.37      .1       0
Bank Sta=190.8,218.37
XS Rating Curve= 0 ,0
Exp/Cntr(USF)=0,0
Exp/Cntr=0.3,0.1

Type RM Length L Ch R = 1 ,9297    ,290.5,295.7,297.7
XS GIS Cut Line= 6
1660600.29940218525836.4440315071660686.96064617525821.232119679
1660761.24658684525807.1855598391660860.92388092525796.618979916
 1660935.8259621525792.828961253 1661023.2076771525788.403773248
#Sta/Elev= 30
       0  948.76     9.2  938.99    15.8  933.13    35.8  920.23    42.5  916.81
    75.7  903.42   108.7  883.34   112.5  881.65   122.5  879.98     146  880.56
   165.9  880.27   172.5  879.41   179.1  880.06     189  879.03  196.98876.8049
   218.7  875.95  233.82876.8045   238.5  878.74   245.1  883.42     255  886.57
   268.2   892.7   281.3  903.05   307.6  919.99   320.7  925.46   330.6  930.62
   376.6   961.4   386.4  969.35     393   973.1   400.5  979.82   426.3  998.25
#Mann= 3 ,-1,0
       0      .1       0  196.98    .045       0  233.82      .1       0
Bank Sta=196.98,233.82
XS Rating Curve= 0 ,0
Exp/Cntr(USF)=0,0
Exp/Cntr=0.3,0.1

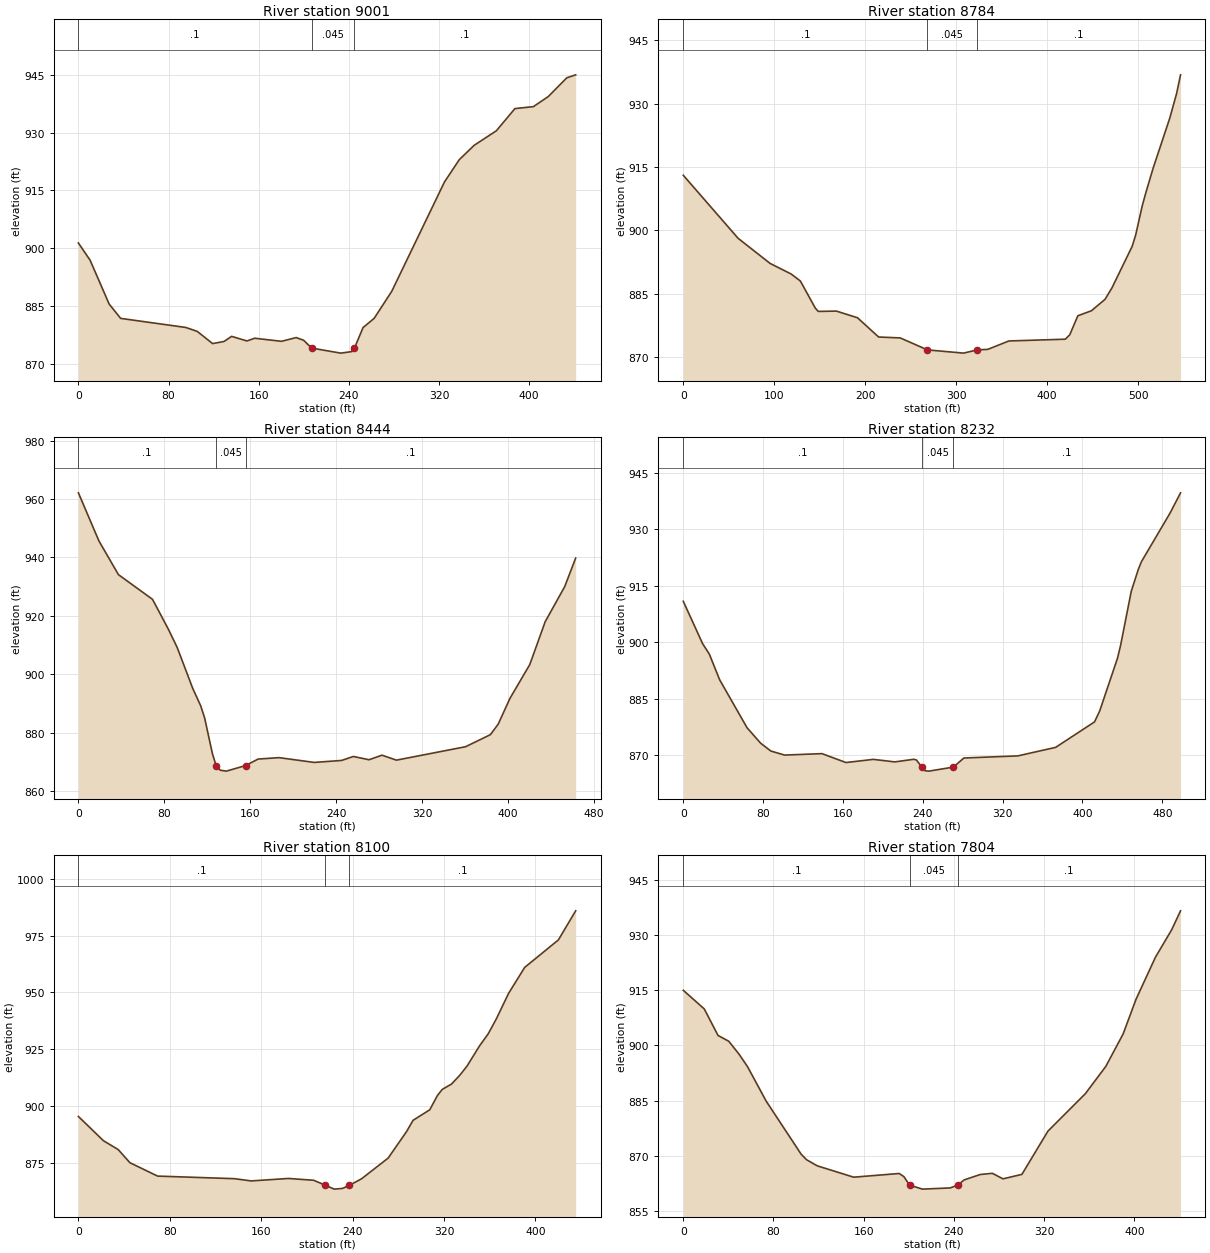
Type RM Length L Ch R = 1 ,9001    ,172.5,216.7,243.9
XS GIS Cut Line= 6
1660645.25436476526039.2034685021660739.59571151526064.391082168
1660817.88853392526085.5662366751660917.59535551526093.378557011
1660992.44920842526098.0566972491661079.77875817   526103.516332
#Sta/Elev= 30
       0  901.38    10.4  896.92    27.3  885.56    37.5  881.85    95.3   879.5
   105.5  878.48   119.1  875.32   129.2  875.87     136  877.19   149.6     876
   156.4  876.71   180.2  875.91   193.3  876.88   199.9  876.18  206.98874.1584
   232.8  872.85   242.7  873.25  245.01  874.16   252.6  879.46   262.5  881.87
   278.1  888.87   324.9  917.21   338.1     923   351.2  926.68   370.9  930.45
   387.4   936.2   403.8  936.71     417  939.32   433.4  944.17   441.3  944.95
#Mann= 3 ,-1,0
       0      .1       0  206.98    .045       0  245.01      .1       0
Bank Sta=206.98,245.01
XS Rating Curve= 0 ,0
Exp/Cntr(USF)=0,0
Exp/Cntr=0.3,0.1

Type RM Length L Ch R = 1 ,8784    ,367.8,340.4,315.9
XS GIS Cut Line= 4
1660528.04265693526143.0320010041660747.65368859526174.506612076
1660721.24432914526351.1192034231660849.45173162526421.327763649
#Sta/Elev= 30
       0  913.05    60.3  898.11    95.4  892.17   118.6  889.65   128.7     888
   145.1  881.58   148.4  880.79   168.3  880.87   191.5  879.29   214.7  874.73
   238.5  874.51   268.4871.6779   308.1  870.91  323.02 871.678   334.7   871.8
   357.9  873.79   419.9  874.21   424.8  875.25   433.7  879.76   448.7  880.96
   463.6  883.66   471.1  886.33   493.5  896.25   497.3  898.92   504.5  905.82
   508.5  908.96   516.6  914.83   534.7  926.55   542.2  932.37   546.6  936.85
#Mann= 3 ,-1,0
       0      .1       0   268.4    .045       0  323.02      .1       0
Bank Sta=268.4,323.02
XS Rating Curve= 0 ,0
Exp/Cntr(USF)=0,0
Exp/Cntr=0.3,0.1

Type RM Length L Ch R = 1 ,8444    ,222.6,211.6,188.4
XS GIS Cut Line= 2
1660346.06691341 526394.831412981660762.83060674526596.472980279
#Sta/Elev= 30
       0  962.12    19.1  945.65    37.3  934.09      69  925.64    83.8  915.38
      92  909.13   106.6     895   113.9  889.15   117.5  885.06   124.8  872.74
  128.18868.7152   132.1  867.09   137.8  866.79  155.77 868.714   167.3  870.92
   186.8  871.41   219.6  869.77   245.1  870.45     256  871.81   270.6  870.69
   282.7  872.25   296.1  870.55   360.5  875.15   383.6  879.28   390.9   882.9
   401.8   891.7   420.3  903.31   434.6  917.96   452.8  929.99     463  939.77
#Mann= 3 ,-1,0
       0      .1       0  128.18    .045       0  155.77      .1       0
Bank Sta=128.18,155.77
XS Rating Curve= 0 ,0
Exp/Cntr(USF)=0,0
Exp/Cntr=0.3,0.1

Type RM Length L Ch R = 1 ,8232    ,121.2,132,152.3
XS GIS Cut Line= 4
1660285.69539598526655.0123628911660452.07436054526704.034736377
1660556.15462626526615.0478073031660735.16510558526672.217877525
#Sta/Elev= 30
       0  910.92    19.3  899.71    26.2  896.85    36.4  890.11    63.9  877.36
    77.5  873.27    87.7  871.19   101.4  870.11     139  870.49     163  868.13
   190.4  868.97     212   868.3   230.9  868.99   233.6  868.82  239.04866.9192
   242.2  865.95   246.1  865.85  270.66866.9167   281.2  869.33   335.2  869.89
   373.1  872.15   412.1  878.91   417.3  881.83   435.1   895.8   438.2  899.19
   448.9  913.56   455.8  919.25     459  921.39   487.8  934.33   498.3   939.7
#Mann= 3 ,-1,0
       0      .1       0  239.04    .045       0  270.66      .1       0
Bank Sta=239.04,270.66
XS Rating Curve= 0 ,0
Exp/Cntr(USF)=0,0
Exp/Cntr=0.3,0.1

Type RM Length L Ch R = 1 ,8100    ,291,295.9,302.7
XS GIS Cut Line= 6
 1660284.2075844526698.4869616961660377.23266082526728.350747127
1660445.00713157526760.4697773641660535.29336832526803.462801624
1660603.00779982526835.7078158741660682.00829799526873.327163208
#Sta/Elev= 30
       0  895.33    21.9  884.65    34.8  880.76    45.1  874.95    69.3  869.06
   136.7  867.92   151.2  866.93   183.8  868.02   205.9  867.22  216.19865.0119
   223.9  863.32   231.2  863.63  237.24 865.012   247.8  867.87   271.1  876.99
   287.2  888.67   292.9  893.63   307.5  898.26   314.2  904.53   318.4  907.23
   326.6  909.62   333.9  913.54   340.2  917.58   351.1  926.44   358.6  931.68
   365.6  938.14   376.5  949.55   390.6  960.99   420.1  973.09   435.2   985.9
#Mann= 3 ,-1,0
       0      .1       0  216.19    .045       0  237.24      .1       0
Bank Sta=216.19,237.24
XS Rating Curve= 0 ,0
Exp/Cntr(USF)=0,0
Exp/Cntr=0.3,0.1

Type RM Length L Ch R = 1 ,7804    ,310,304.2,263.9
XS GIS Cut Line= 6
  1660156.520106526798.1323968321660203.26968442 526872.09812817
1660243.34112659526935.4979357571660303.82985076527015.566017091
1660369.36351234527062.6804241691660452.94044492527112.840428844
#Sta/Elev= 30
       0  914.97    18.6  909.92    30.8  902.73    40.3  901.16    49.3  897.71
      57  894.25    73.5  884.92   104.5  870.53   109.3  869.03   118.8  867.37
   151.1  864.29   191.5  865.29   195.6  864.45  200.69 862.142   212.1  861.05
   236.8  861.38   243.4  862.14   249.1  863.55   263.3  865.01   274.1  865.34
   283.5  863.84   300.3  865.05   323.4  876.78   356.6  886.94   374.7  894.33
   390.1  903.14   401.5  912.52   418.7  923.92   433.1  931.37     441  936.52
#Mann= 3 ,-1,0
       0      .1       0  200.69    .045       0   243.4      .1       0
Bank Sta=200.69,243.4
XS Rating Curve= 0 ,0
Exp/Cntr(USF)=0,0
Exp/Cntr=0.3,0.1

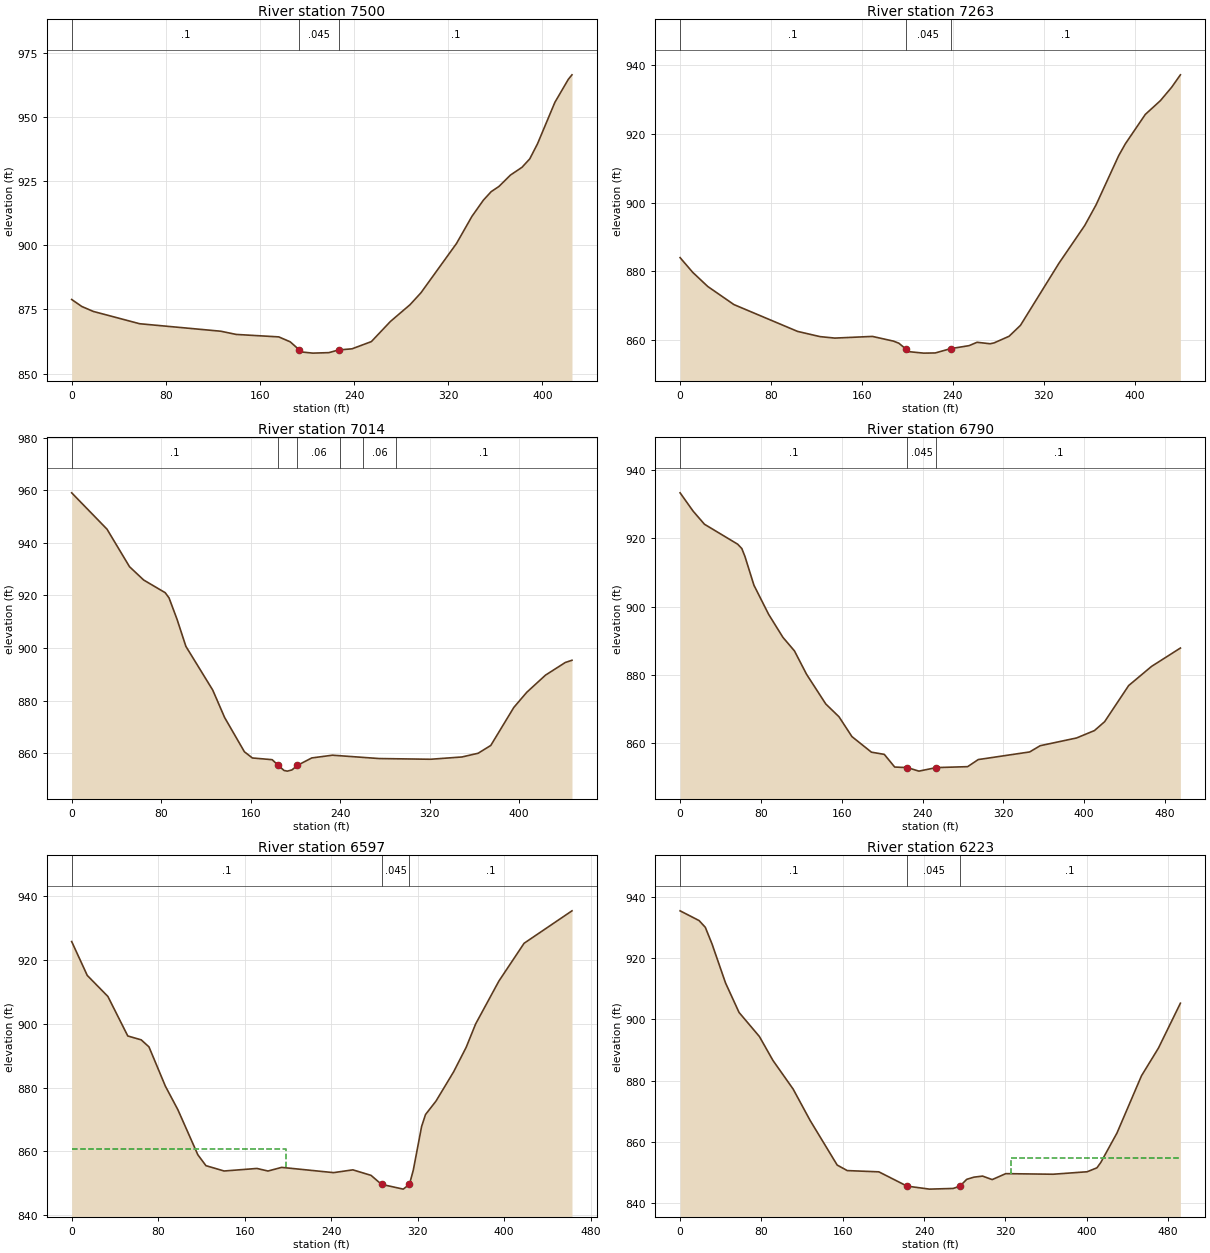
Type RM Length L Ch R = 1 ,7500    ,220.4,237.2,249.9
XS GIS Cut Line= 6
1660016.78580542 527244.496333511660104.36863551527246.731565252
1660179.35667451527245.0271723421660279.28823318527241.325080007
1660354.25232209527238.9655046761660441.81612334527239.073444083
#Sta/Elev= 30
       0  878.89     8.6  876.17    18.4  874.24    57.8  869.45   126.7  866.54
   139.8  865.29     176  864.33   185.7  862.42  193.55859.2383   195.7  858.45
   204.9  858.01   218.6   858.2   226.8  859.24   238.3  859.69   254.7   862.5
   270.9  870.34   287.6  876.88   296.9  881.54     327  900.66   340.1   911.2
   349.9  917.56   356.5  920.87   363.1  922.89   372.9  927.33   382.7  930.35
   389.3  933.63   395.9  939.51   410.7  955.68   422.1  964.62   425.2  966.36
#Mann= 3 ,-1,0
       0      .1       0  193.55    .045       0   226.8      .1       0
Bank Sta=193.55,226.8
XS Rating Curve= 0 ,0
Exp/Cntr(USF)=0,0
Exp/Cntr=0.3,0.1

Type RM Length L Ch R = 1 ,7263    ,264.8,248.7,232.5
XS GIS Cut Line= 5
1659991.35940249527433.041497916 1660078.3884279527442.106768489
1660170.81138113527449.8770941641660233.13496272527510.745865777
1660403.62460491527481.108240627
#Sta/Elev= 30
       0  883.97    11.1  879.69    24.3  875.58    47.4  870.29   103.4  862.48
   123.2  860.96   136.3  860.53   169.3  861.02   187.9  859.64   192.5  859.05
  198.42857.4552   201.6  856.57   214.4  856.15   224.6   856.2  238.15857.4543
   254.4  858.33   261.4  859.31   272.9  858.88   276.3  859.12   289.6  861.06
   299.6  864.24   333.4  882.29   356.2  893.34   366.2  899.37   386.1   913.7
     392  917.16   409.5  925.69   422.8  929.71   432.8  933.65   440.4  937.23
#Mann= 3 ,-1,0
       0      .1       0  198.42    .045       0  238.15      .1       0
Bank Sta=198.42,238.15
XS Rating Curve= 0 ,0
Exp/Cntr(USF)=0,0
Exp/Cntr=0.3,0.1

Type RM Length L Ch R = 1 ,7014    ,244,223.7,208.8
XS GIS Cut Line= 2
1659997.13666617527791.7996735741660411.49564593527623.591047749
#Sta/Elev= 30
       0     959    31.6  945.18    51.7  930.93    64.3  925.89    83.6  921.06
      87  919.11    94.2  910.93   102.1  900.66   126.1  884.05   136.7  873.65
   154.4  860.62   161.5  858.27   179.2  857.62   184.7 855.456   189.8  853.52
   192.8  853.27   196.9  853.73  201.79855.4556   214.6  858.28   233.1  859.32
   274.8  858.05   320.8  857.78   348.9  858.65   363.3  860.06   374.6  863.02
   395.2  877.46   406.8  883.23   423.5  889.73   441.2  894.54   447.2  895.39
#Mann= 6 ,-1,0
       0      .1       0   184.7    .045       0  201.79     .06       0
     240      .1       0     260     .06       0     290      .1       0
Bank Sta=184.7,201.79
XS Rating Curve= 0 ,0
Exp/Cntr(USF)=0,0
Exp/Cntr=0.3,0.1

Type RM Length L Ch R = 1 ,6790    ,174.2,193.1,201.6
XS GIS Cut Line= 4
1660185.39267552527988.930995052 1660346.5400569527875.579615974
  1660307.205846 527748.27570703 1660423.0769106527630.919115957
#Sta/Elev= 30
       0  933.38    12.9     928    24.1  924.16      57   918.3    61.1  917.02
    64.2  914.69    73.1  906.25    87.7  897.68   101.8  890.95   113.2  886.98
   125.2   880.1   144.2   871.4   157.3  867.64   170.1  861.82   189.4  857.25
   202.1  856.61   212.4  852.89  225.02852.7192   236.4  851.69   253.6  852.73
   284.6     853   295.1  855.08     346  857.32   356.4  859.15   392.4  861.42
   410.1  863.59   420.2   866.2     444  876.81   466.6  882.42   495.2  887.82
#Mann= 3 ,-1,0
       0      .1       0  225.02    .045       0   253.6      .1       0
Bank Sta=225.02,253.6
XS Rating Curve= 0 ,0
Exp/Cntr(USF)=0,0
Exp/Cntr=0.3,0.1

Type RM Length L Ch R = 1 ,6597    ,337.3,374.5,416.3
XS GIS Cut Line= 4
1660278.64683026528044.6623840931660404.90445176527970.518503502
1660482.00436318527907.8864109221660620.06045614527740.388131416
#Sta/Elev= 30
       0  925.67    14.4  915.08    33.5  908.49    51.9  896.13    64.3  894.92
    71.5  892.72    86.7  880.41    98.2  873.09   116.7  858.97   124.2  855.56
     141  853.89   171.4  854.69   181.6  853.88   194.2  855.02   242.3  853.38
   260.1  854.25   276.9  852.53  286.61849.7178   306.7  848.22  312.46849.7214
     316  854.15   323.7  867.82   327.3  871.55     337  875.76   353.3  884.91
   364.9  892.57   373.7  899.91   395.2  913.31   418.5  925.13   462.8  935.28
#Mann= 3 ,-1,0
       0      .1       0  286.61    .045       0  312.46      .1       0
#XS Ineff= 2 , 0
          198.56  860.67
Permanent Ineff=
       F       F
Bank Sta=286.61,312.46
XS Rating Curve= 0 ,0
Exp/Cntr(USF)=0,0
Exp/Cntr=0.3,0.1

Type RM Length L Ch R = 1 ,6223    ,240.8,222.9,186.4
XS GIS Cut Line= 4
1660276.51378894 528096.742484411660444.03660331528124.434865862
1660465.47751918528246.8903188731660660.08569993528283.126474082
#Sta/Elev= 30
       0  935.41    18.7  932.23    24.8  930.03    31.4  924.61    44.7  911.87
      58  902.25      78   894.4    91.3  886.61   111.2  877.24   127.9  867.01
   154.5  852.46   164.4  850.65   195.5  850.24   223.2 845.585   245.3   844.6
   268.6  844.82  275.31845.5833   281.9  847.79     289  848.51   297.5  848.85
     307  847.71   320.3  849.65     367  849.46   400.4  850.27     410  851.55
   413.8   853.3   429.7   862.9   453.8  881.57   470.5  890.62   492.1  905.26
#Mann= 3 ,-1,0
       0      .1       0   223.2    .045       0  275.31      .1       0
#XS Ineff= 2 , 0
                          325.63           854.8
Permanent Ineff=
       F       F
Bank Sta=223.2,275.31
XS Rating Curve= 0 ,0
Exp/Cntr(USF)=0,0
Exp/Cntr=0.3,0.1

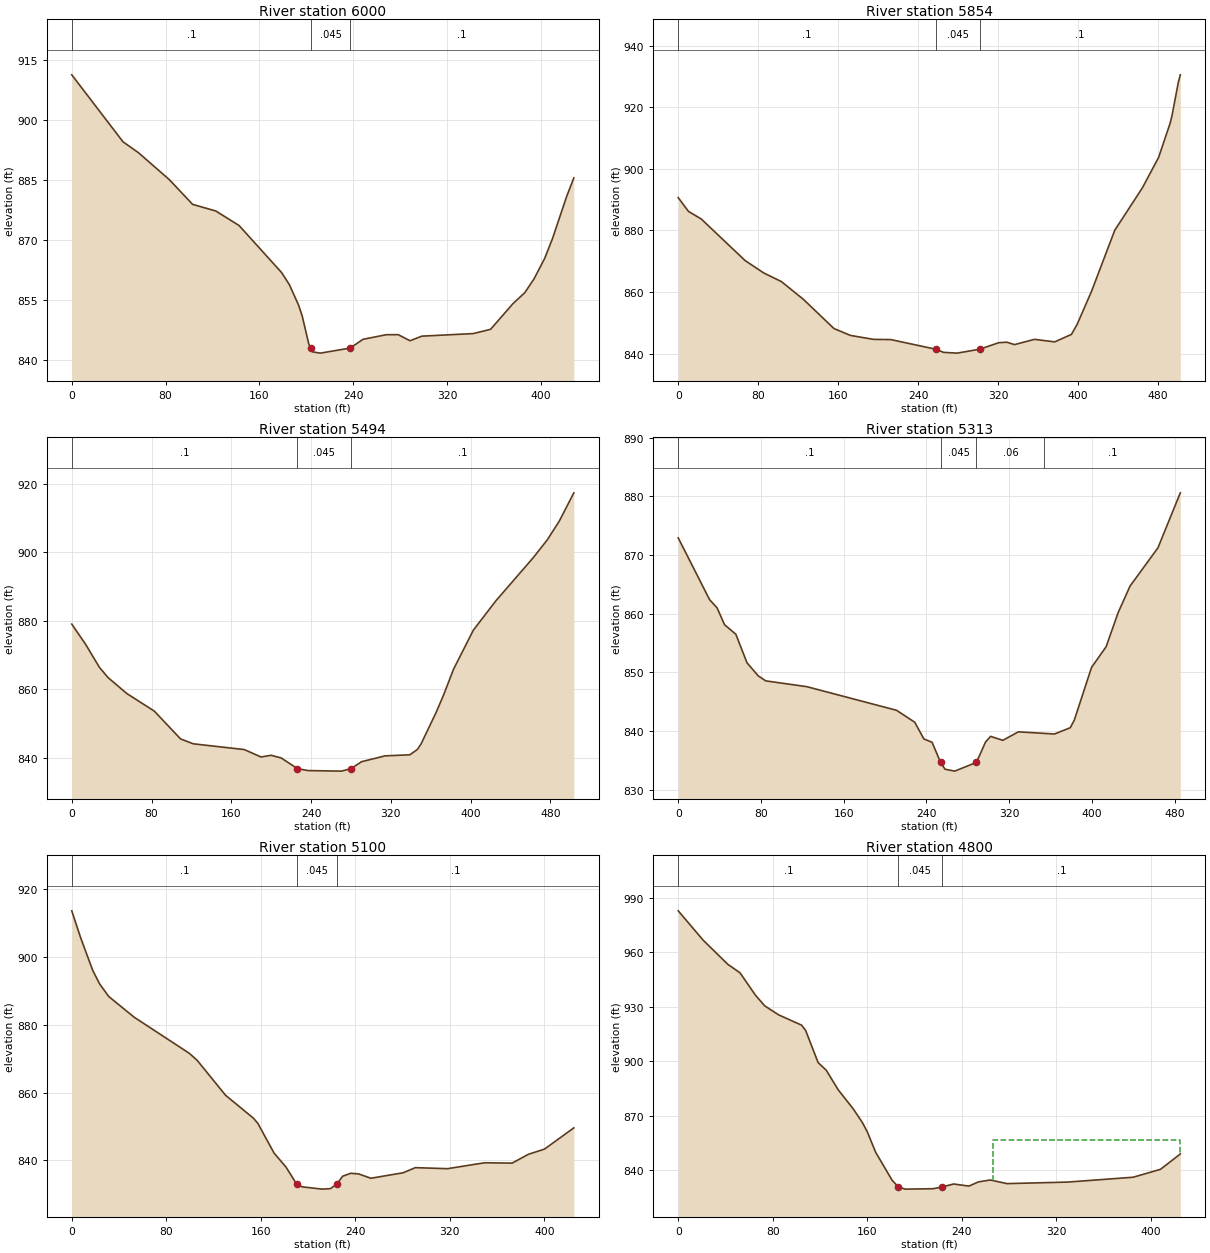
Type RM Length L Ch R = 1 ,6000    ,163.1,146.2,128.7
XS GIS Cut Line= 6
1660145.96664943 528370.090210931660232.95433635528379.544916421
1660307.51521084528387.6502151791660406.90838476528398.652161673
1660480.37149243 528416.080276431660567.96941434 528437.73246409
#Sta/Elev= 30
       0  911.36    43.7   894.6    56.9  891.87    83.1  885.16   103.1  878.94
   122.9  877.28   142.7  873.65     179  861.87   185.6  858.85   193.5  853.69
   196.5  851.05   202.1  844.06   203.8  842.99   205.4  842.03     212  841.72
   237.5 842.988   248.3  845.17   268.2  846.33   278.4  846.34   288.5  844.82
   298.6  845.97   342.4  846.61   357.2  847.68   376.2  854.08   386.4  856.86
   394.3  860.33   403.3  865.41     410  870.39   422.2  881.03   428.2  885.56
#Mann= 3 ,-1,0
       0      .1       0   203.8    .045       0   237.5      .1       0
Bank Sta=203.8,237.5
XS Rating Curve= 0 ,0
Exp/Cntr(USF)=0,0
Exp/Cntr=0.3,0.1

Type RM Length L Ch R = 1 ,5854    ,290.3,360.1,396
XS GIS Cut Line= 4
1660134.88957185528441.9656897681660315.36423719528577.360150686
1660388.64556621528504.7721286351660558.38516495528540.699753203
#Sta/Elev= 30
       0  890.64    10.3  886.16      23  883.72    66.8  870.24    85.5  866.19
   103.2  863.38   125.1  857.65   155.8  848.13   172.2   845.9   195.3  844.61
   212.6  844.54  257.69841.4097   265.4  840.39     279  840.14  301.56841.4094
   320.7  843.53   328.8  843.69   336.4  842.91   356.5  844.62   376.6  843.79
   393.4  846.23   399.1  849.49   413.5  860.23   436.7  880.04   464.4  893.86
   480.6  903.72   492.1   914.8     494   917.3   500.4  928.24   502.3  930.54
#Mann= 3 ,-1,0
       0      .1       0  257.69    .045       0  301.56      .1       0
Bank Sta=257.69,301.56
XS Rating Curve= 0 ,0
Exp/Cntr(USF)=0,0
Exp/Cntr=0.3,0.1

Type RM Length L Ch R = 1 ,5494    ,216,181,162.2
XS GIS Cut Line= 5
1660075.84979426528546.3535907241660136.80538102528609.128399563
1660165.66095785528669.7579559791660128.83020296528833.311139115
1660287.44916195528920.995415878
#Sta/Elev= 30
       0  879.01      14  873.06    27.7  866.39    36.4  863.39    55.2  858.73
    82.8  853.59   109.1  845.47   121.9  844.04     173  842.36   189.8  840.19
   199.9  840.69     210  839.91  226.29836.8004   236.9  836.22   270.5  836.06
  280.11836.7996   290.7  838.82   314.2  840.52     339  840.83   346.6  842.39
   350.3  844.02   365.3  853.15   372.8  858.24   382.8  865.81   402.7  877.23
   425.2  885.78   462.5  898.32     477  903.67     489  909.15   503.5  917.36
#Mann= 3 ,-1,0
       0      .1       0  226.29    .045       0  280.11      .1       0
Bank Sta=226.29,280.11
XS Rating Curve= 0 ,0
Exp/Cntr(USF)=0,0
Exp/Cntr=0.3,0.1

Type RM Length L Ch R = 1 ,5313    ,218,212.5,209
XS GIS Cut Line= 3
1659878.23797202528669.8907719571659972.09353435528873.244490336
1660194.69967577529010.418004509
#Sta/Elev= 30
       0  872.94    30.3  862.41    37.6  860.99    44.8  858.13    55.7  856.51
    66.5  851.64    77.4   849.4    84.6  848.56   124.3  847.57   211.1  843.54
   228.7   841.5   237.5  838.65   245.4  838.09  253.61834.6558   257.9   833.5
   267.3  833.17  288.28834.6552   297.1  838.13     302   839.1   313.8  838.42
   328.9  839.87   363.8   839.5     379  840.57   382.9  841.86   399.6  850.86
   413.7  854.39   425.3  860.19   436.8  864.72   463.8  871.25   485.4  880.62
#Mann= 4 ,-1,0
       0      .1       0  253.61    .045       0  288.28     .06       0
  353.97      .1       0
Bank Sta=253.61,288.28
XS Rating Curve= 0 ,0
Exp/Cntr(USF)=0,0
Exp/Cntr=0.3,0.1

Type RM Length L Ch R = 1 ,5100    ,313.1,300,291.9
XS GIS Cut Line= 6
1659709.79330917529026.690603763 1659794.0700435529050.242065832
1659866.11025375529071.1042288391659962.10973367529099.106469423
1660034.10958968 529120.106755511660118.11040592529144.603425667
#Sta/Elev= 30
       0  913.58     7.4  905.77    17.7  896.06    23.5  892.08    31.3  888.33
    52.8  882.23    99.5  871.58     106  869.58   130.2  859.21   153.7  852.48
   157.5  850.95   171.2   842.2   181.4  838.03  190.43832.9807   195.1  832.22
   212.2  831.55     219   831.7  224.24832.9801   229.3  835.35   236.1  836.22
     243  836.02   253.2  834.76   280.5  836.37   290.8  837.88   318.1  837.58
   349.5  839.32   372.8  839.22   386.5  841.81   400.2  843.35     425  849.61
#Mann= 3 ,-1,0
       0      .1       0  190.43    .045       0  224.24      .1       0
Bank Sta=190.43,224.24
XS Rating Curve= 0 ,0
Exp/Cntr(USF)=0,0
Exp/Cntr=0.3,0.1

Type RM Length L Ch R = 1 ,4800    ,321.3,321.9,322.7
XS GIS Cut Line= 6
1659733.22698934529444.1579446791659815.78194234 529415.15636225
1659886.54361184529390.2978161721659980.89119217529357.153525501
1660051.65056509529332.2956355961660134.20420575 529303.29470934
#Sta/Elev= 30
       0  982.77      21  966.68    41.9  953.36    52.3  948.63    65.2  936.46
    73.2  930.44      85  925.48   104.5  919.77   107.9  916.83   118.4  899.21
   125.3  894.99   135.4  884.22   148.3  873.57     156  866.05   160.1  860.98
   167.1  849.83     181  834.46  186.32830.7094   192.1  829.51   215.7  829.73
  223.45  830.71   233.1  832.34   246.1  831.18     254  833.48   264.1  834.54
   278.3  832.55   329.4  833.38   385.1  836.06   408.2  840.41     425  848.87
#Mann= 3 ,-1,0
       0      .1       0  186.32    .045       0  223.45      .1       0
#XS Ineff= 2 , 0
                          266.53          856.55
Permanent Ineff=
       F       F
Bank Sta=186.32,223.45
XS Rating Curve= 0 ,0
Exp/Cntr(USF)=0,0
Exp/Cntr=0.3,0.1

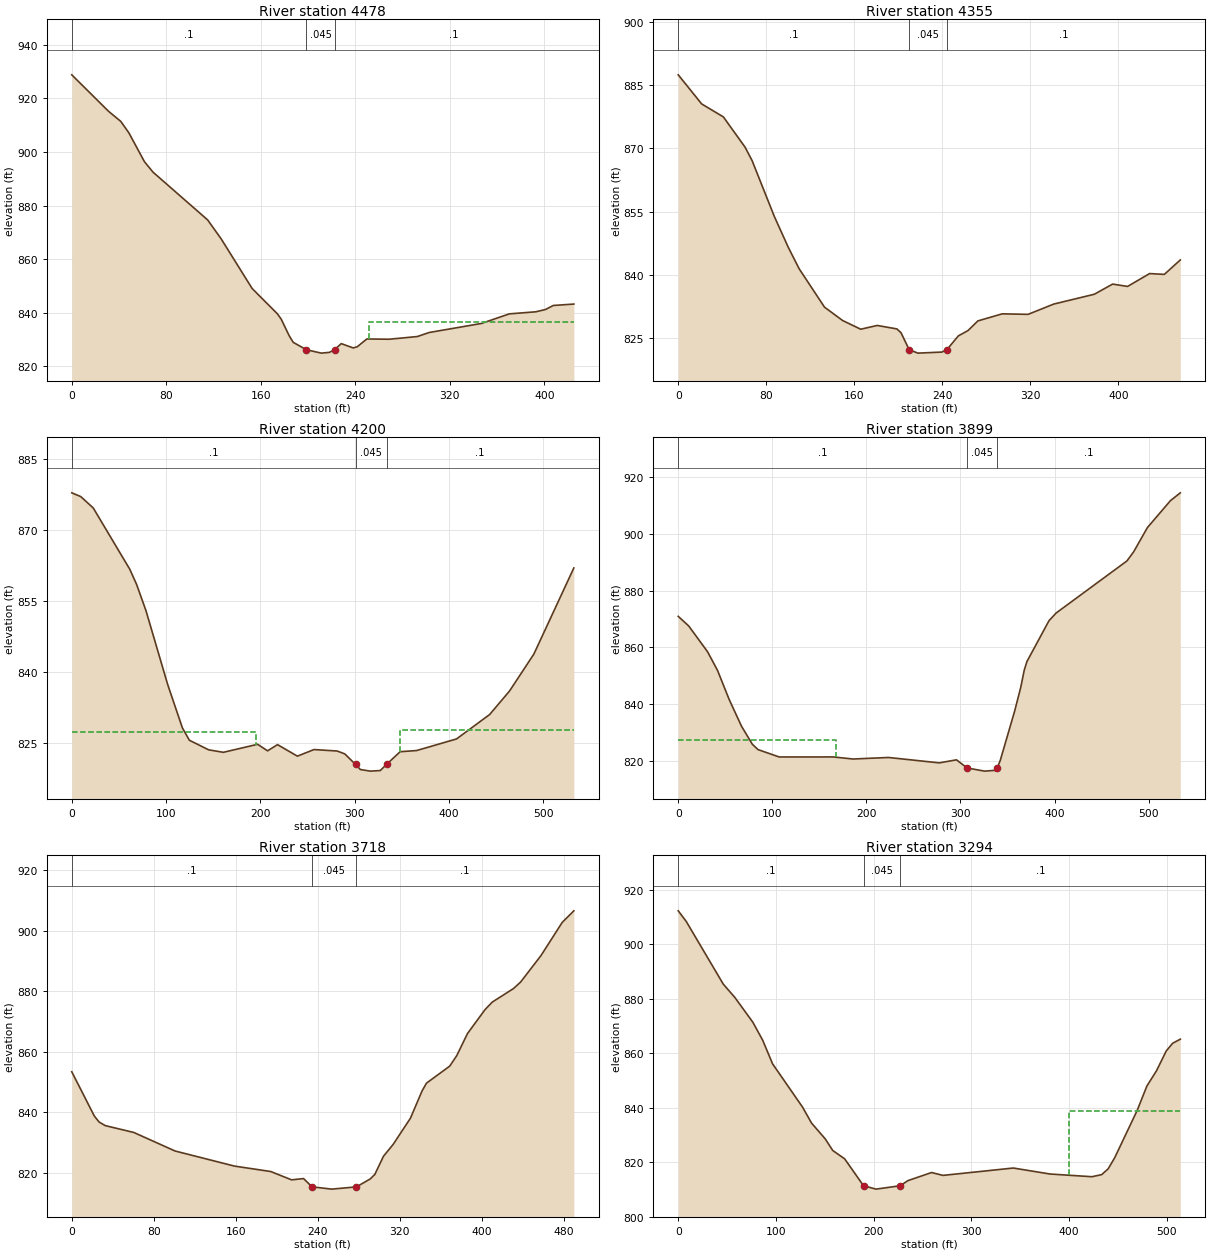
Type RM Length L Ch R = 1 ,4478    ,139,122.9,114.7
XS GIS Cut Line= 6
1659844.43121493529727.8910047351659928.50880266529703.551486486
1660001.16876234529684.9629409841660098.04881791529660.178213649
1660170.70877759  529641.59065241660255.45368683529619.770157986
#Sta/Elev= 30
       0  928.71    31.2  915.09    41.5  911.35    48.3  907.12    61.5  896.35
    68.8  892.42     115  874.64   126.5  867.55   152.7  849.06     174  839.66
   177.3  837.64   184.1  831.41   187.5  828.98  198.67826.2392   211.2  824.98
     218  825.26  222.44826.2383   228.1  828.52   238.3  826.91   241.7  827.37
   249.8  830.26   268.7  830.16   292.5  831.16   302.6  832.67   346.7  836.03
   370.4  839.61   392.7  840.38   400.9  841.22   407.6  842.74     425  843.27
#Mann= 3 ,-1,0
       0      .1       0  198.67    .045       0  222.44      .1       0
#XS Ineff= 2 , 0
                          251.99          836.76
Permanent Ineff=
       F       F
Bank Sta=198.67,222.44
XS Rating Curve= 0 ,0
Exp/Cntr(USF)=0,0
Exp/Cntr=0.3,0.1

Type RM Length L Ch R = 1 ,4355    ,139.2,155.2,160.8
XS GIS Cut Line= 4
1659889.27543369529842.4762352151660066.05308353529835.048602869
1660119.53203643529742.9459617741660288.88205392 529708.77885298
#Sta/Elev= 30
       0  887.39    21.3   880.5      41  877.43    60.7  870.28    67.2  867.03
    87.3  853.87   100.1   846.5   109.9  841.47   132.9   832.4   149.3  829.24
   165.8  827.17   180.8  828.06   198.7  827.24   202.5  826.31  209.76 822.346
   217.7  821.51   239.6  821.76  244.19822.3484   254.5  825.59   263.2  826.83
   272.3  829.14   294.4  830.81   317.9  830.69   341.3  833.13     378  835.44
   394.7  837.85   408.3   837.3   428.3  840.34   441.7  840.15   456.2  843.57
#Mann= 3 ,-1,0
       0      .1       0  209.76    .045       0  244.19      .1       0
Bank Sta=209.76,244.19
XS Rating Curve= 0 ,0
Exp/Cntr(USF)=0,0
Exp/Cntr=0.3,0.1

Type RM Length L Ch R = 1 ,4200    ,276.5,300.8,322.3
XS GIS Cut Line= 6
1659835.30018396529964.1076308021660029.93932243529975.897694841
1660099.92179401529948.9262920921660193.23164676529912.963437513
1660263.21379025529885.9917066691660344.85962434529854.524578005
#Sta/Elev= 30
       0  877.77     9.6  876.97    22.8  874.57    61.5  861.66    68.8  858.43
    78.7  852.91   101.7  837.35   117.3   828.2   124.7  825.58   145.2  823.55
   160.8  823.03   197.1  824.72   207.7  823.34   218.2  824.65   239.3  822.22
   256.9  823.61   281.5   823.3   289.6  822.69  300.95820.4734   306.1   819.4
   316.7  819.06   327.2  819.18  333.83820.4727   348.3  823.16   365.7   823.4
   408.1  825.85   443.2     831   464.3  835.96   490.1  843.75   532.5  861.92
#Mann= 3 ,-1,0
       0      .1       0  300.95    .045       0  333.83      .1       0
#XS Ineff= 2 , 0
          195.81   827.3   348.3          827.79
Permanent Ineff=
       F       F
Bank Sta=300.95,333.83
XS Rating Curve= 0 ,0
Exp/Cntr(USF)=0,0
Exp/Cntr=0.3,0.1

Type RM Length L Ch R = 1 ,3899    ,183.9,180.5,175
XS GIS Cut Line= 6
1659847.13016559529980.9103502811660012.44723143530085.308893338
1660057.69681284530145.9649400121660107.69441625 530232.58418934
1660144.11724368530298.146394178 1660188.1204365530373.787319005
#Sta/Elev= 30
       0  870.93    11.1  867.56    31.2  858.45    41.8  851.86    54.1  841.67
    67.2  832.25    78.8  825.84    84.8  823.97   107.3  821.37   164.7  821.38
   185.8  820.65   223.5  821.19   277.5  819.29   295.8  820.36  307.08817.4915
   325.6  816.38   337.5  816.67  339.08817.4889   342.4  820.26   357.5  837.41
     364  845.79   367.8  851.96   370.6  854.96   394.1  869.39   401.6  872.08
     477  890.47   484.1  893.68   498.8  902.25   523.2  911.71   533.7  914.47
#Mann= 3 ,-1,0
       0      .1       0  307.08    .045       0  339.08      .1       0
#XS Ineff= 2 , 0
          168.09  827.49
Permanent Ineff=
       F       F
Bank Sta=307.08,339.08
XS Rating Curve= 0 ,0
Exp/Cntr(USF)=0,0
Exp/Cntr=0.3,0.1

Type RM Length L Ch R = 1 ,3718    ,458.8,424.4,393
XS GIS Cut Line= 4
1659764.83558614530121.1762022561659852.10142544530208.751911676
1659981.56064543530341.2522192231660153.46041562530397.918729687
#Sta/Elev= 30
       0  853.38      22  838.73    26.6  836.76    32.7  835.55    60.5  833.29
   100.8  827.15   158.8  822.15   194.1  820.36   214.5   817.6   226.2  818.02
  234.41  815.29   253.7  814.53   277.7  815.27   291.1  817.87   295.7  819.39
   304.2  825.44   313.5  829.29   330.5  838.03   341.7  846.96   346.1  849.61
   368.8  855.25   375.7  858.75   386.1  866.01   403.2  873.93   410.3  876.44
     431  880.92   437.9  883.05   457.8  891.82   478.6  902.84   489.9  906.65
#Mann= 3 ,-1,0
       0      .1       0  234.41    .045       0   277.7      .1       0
Bank Sta=234.41,277.7
XS Rating Curve= 0 ,0
Exp/Cntr(USF)=0,0
Exp/Cntr=0.3,0.1

Type RM Length L Ch R = 1 ,3294    ,285,290.2,287.6
XS GIS Cut Line= 6
1659649.44500467530776.9400560111659696.64340109530703.261397585
 1659735.8693725530639.3369847541659798.04411693530560.163258582
  1659906.603283530526.6042705921660042.99080551530510.466179505
#Sta/Elev= 30
       0  912.23     8.1  908.39    46.1  885.35      58  880.44    76.5   871.3
    86.5  864.74    96.6  856.09   127.4  840.15   136.5  834.36   150.5  828.56
   158.2   824.3   170.4  821.24  189.75 811.363   202.5  810.12  227.33811.3624
   235.2  813.24   259.4  816.21   271.1  815.16   343.1  817.86   380.8  815.66
   423.7  814.67   433.6  815.45   440.2  817.55   446.9  821.62     470  839.05
   479.9  847.96   489.8   853.6   499.7  860.82   506.3  863.64   514.1  865.14
#Mann= 3 ,-1,0
       0      .1       0  189.75    .045       0  227.33      .1       0
#XS Ineff= 2 , 0
                          399.89          838.83
Permanent Ineff=
       F       F
Bank Sta=189.75,227.33
XS Rating Curve= 0 ,0
Exp/Cntr(USF)=0,0
Exp/Cntr=0.3,0.1