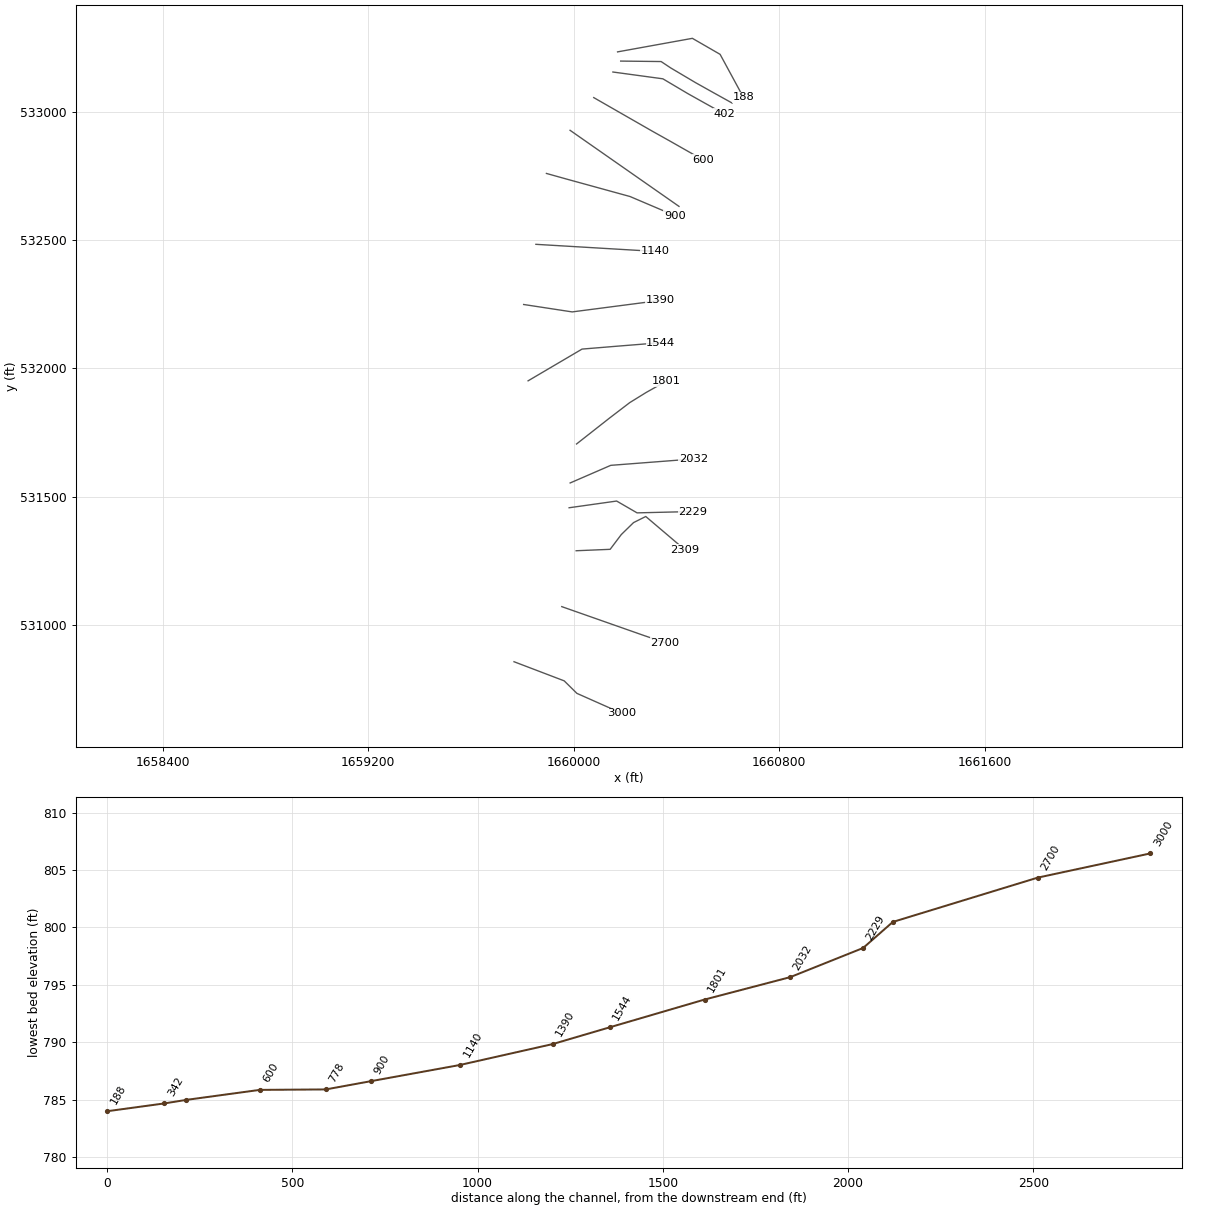
HEC-RAS study StullRn.prj: StullRn

--- StullRn.g01 (geometry) --- (continued)

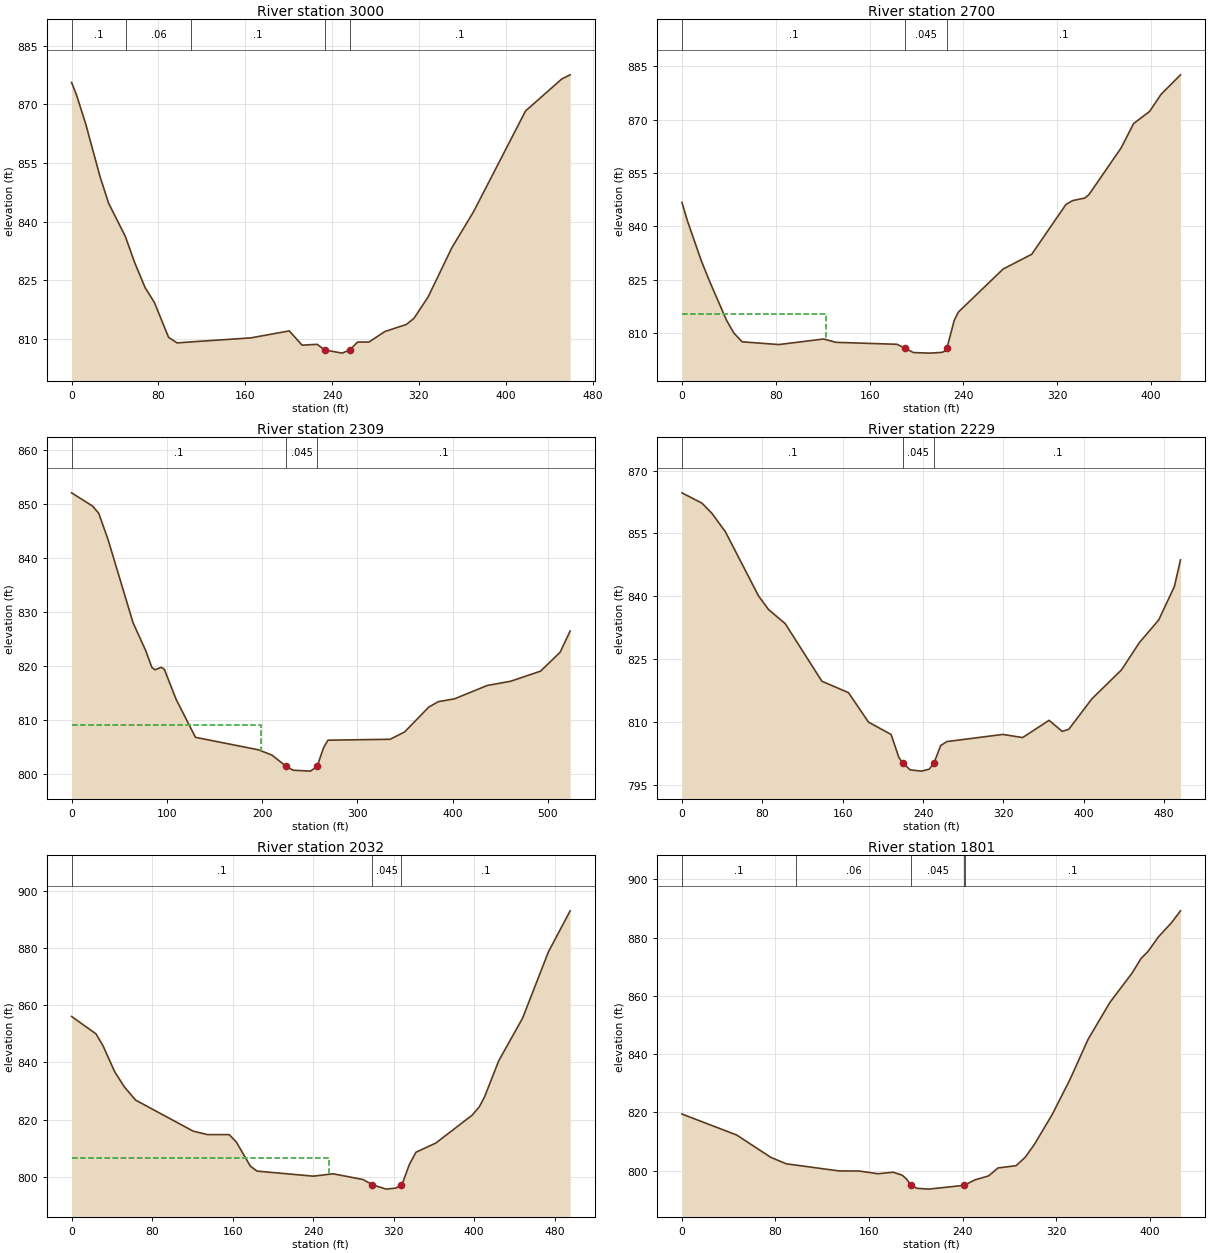
Type RM Length L Ch R = 1 ,3000    ,295.3,304,308.7
XS GIS Cut Line= 4
1659768.16351544530858.579255832 1659963.4892526530784.125795815
1660012.92654851530735.4170679791660188.32852203530657.522081287
#Sta/Elev= 30
       0  875.57     4.6  872.34    13.1   864.9    26.1  851.63    34.1  844.74
    49.5  836.27      58  829.66    67.8  823.14    76.3  819.39    89.4  810.46
    97.3  809.05     110  809.31   165.1  810.33   200.6  812.12   212.4  808.47
   226.3  808.69   233.3  807.24   249.4  806.44   256.5   807.3   263.5  809.26
     274  809.28   288.7  811.96   308.5  813.77   315.5  815.33   328.6  820.83
   350.4  833.36   370.4  842.56   418.3  868.29   451.8  876.49   459.4  877.52
#Mann= 5 ,-1,0
       0      .1       0      50     .06       0     110      .1       0
   233.3    .045       0   256.5      .1       0
Bank Sta=233.3,256.5
XS Rating Curve= 0 ,0
Exp/Cntr(USF)=0,0
Exp/Cntr=0.3,0.1

Type RM Length L Ch R = 1 ,2700    ,371.4,391.2,405.3
XS GIS Cut Line= 6
1659954.00870001531073.0267341731660036.56135643531044.021870926
1660107.32105742531019.1603720931660201.66732542530986.012144417
1660272.42702642530961.1513017571660355.25527284530932.930557668
#Sta/Elev= 30
       0  846.69     4.7   841.5    16.5  830.31    23.5  824.59    38.1  813.51
    44.3  809.97    51.3  807.51    82.6  806.74   120.8   808.3   131.3  807.37
   183.4  806.81  189.94805.7436   197.3  804.49   211.2  804.33   221.7  804.54
   225.2  805.05   225.9805.7413   232.1   813.5   235.6  815.85   273.8  827.97
   298.2  832.12   327.3   846.1     333   847.2   343.4  847.92     347   848.9
   374.6  862.12     385  868.85   398.7  872.28   408.4  877.07     425  882.56
#Mann= 3 ,-1,0
       0      .1       0  189.94    .045       0   225.9      .1       0
#XS Ineff= 2 , 0
           123.1  815.36
Permanent Ineff=
       F       F
Bank Sta=189.94,225.9
XS Rating Curve= 0 ,0
Exp/Cntr(USF)=0,0
Exp/Cntr=0.3,0.1

Type RM Length L Ch R = 1 ,2309    ,101.6,80.3,62
XS GIS Cut Line= 6
1660010.04533334531290.5545143341660142.35781086531296.092770639
 1660185.6757627531353.4890568331660233.32550973531400.055855065
1660280.97525676531423.8807285791660432.87924191531294.886309518
#Sta/Elev= 30
       0  852.09    21.9  849.65    28.5   848.3    38.3  843.42    64.6  827.96
    77.7  822.87    84.3  819.71    87.6  819.26    94.1  819.73    97.4  819.36
   109.8  813.77   130.1  806.74   196.3  804.42   210.3  803.45  225.33801.3626
   232.5  800.64   250.8  800.47  257.84801.3632   264.6  804.82   269.2  806.21
   334.5  806.38   349.7  807.74     375  812.34   385.1  813.36   402.1  813.88
   436.5  816.36   461.2  817.15   492.5  819.02     513  822.53   523.5  826.46
#Mann= 3 ,-1,0
       0      .1       0  225.33    .045       0  257.84      .1       0
#XS Ineff= 2 , 0
          198.84  809.05
Permanent Ineff=
       F       F
Bank Sta=225.33,257.84
XS Rating Curve= 0 ,0
Exp/Cntr(USF)=0,0
Exp/Cntr=0.3,0.1

Type RM Length L Ch R = 1 ,2229    ,187.4,196.8,204.7
XS GIS Cut Line= 4
1659982.60617553531457.8783690141660167.66500373531484.016621584
1660247.12529154531438.0132970611660464.59555292531443.240947575
#Sta/Elev= 30
       0  864.69      20  862.21    29.9  859.78    43.2  855.41    76.3  840.04
    86.3  836.78   102.8  833.44   139.3  819.68   165.8  816.94   185.7  809.91
   208.2  806.96   215.8  801.53   219.6  800.19   227.2   798.5   238.5   798.2
   246.1  798.67  250.95  800.19   257.5   804.3   263.7  805.26   319.4  806.97
   339.1  806.22   365.4  810.34   378.5  807.69   385.1  808.21     408  815.47
   437.6  822.42   455.2  828.88   474.5  834.31   490.1  842.29   496.2  848.67
#Mann= 3 ,-1,0
       0      .1       0   219.6    .045       0  250.95      .1       0
Bank Sta=219.6,250.95
XS Rating Curve= 0 ,0
Exp/Cntr(USF)=0,0
Exp/Cntr=0.3,0.1

Type RM Length L Ch R = 1 ,2032    ,222.5,230.9,241.8
XS GIS Cut Line= 3
1659986.68792235 531554.412975921660144.74751347531622.990936483
1660466.78956706531647.840246188
#Sta/Elev= 30
       0  856.09    24.3  849.99    31.4   845.7    42.8  836.76    52.3   831.5
    63.6  826.82   120.8  815.95   135.1  814.74   156.6  814.74   163.7  812.13
   177.6  803.71   184.2  801.97   240.1   800.2   259.9  801.02   289.5  799.02
  298.91797.1864   312.5  795.66   322.4  796.03  327.25 797.185     329  798.02
   335.5  804.23   342.1  808.57   361.9   811.8   398.1  821.59   405.2  824.55
   410.3  827.97   424.4  840.62     448  855.46   473.7  878.69   495.3  893.06
#Mann= 3 ,-1,0
       0      .1       0  298.91    .045       0  327.25      .1       0
#XS Ineff= 2 , 0
          255.96  806.65
Permanent Ineff=
       F       F
Bank Sta=298.91,327.25
XS Rating Curve= 0 ,0
Exp/Cntr(USF)=0,0
Exp/Cntr=0.3,0.1

Type RM Length L Ch R = 1 ,1801    ,265.4,256.2,240.3
XS GIS Cut Line= 6
1660011.53155084531706.1068328321660080.33390668531760.166764095
1660139.30787009531806.5036136661660218.76571642531867.234463334
1660282.97556175531906.9069561661660360.01215309531950.221830174
#Sta/Elev= 30
       0  819.48    46.8  812.28      76  804.62    89.2   802.4   134.4  799.95
   151.1  799.94   167.7  798.99   180.7  799.51   188.4  798.49   192.1  797.17
  195.95795.0116   200.8  794.01   210.8  793.71  241.27795.0092   250.6  796.89
   262.3  798.25   270.4  800.98   285.8  801.75   293.6  804.64   301.3  808.96
   316.7  819.32   332.1   831.5   347.3  845.05   366.1  857.81     385  867.83
   392.5  872.76   398.8  875.33   407.5  880.23   418.8  885.16   426.4  889.19
#Mann= 5 ,-1,0
       0      .1       0    97.5     .06       0  195.95    .045       0
  241.27     .06       0   242.5      .1       0
Bank Sta=195.95,241.27
XS Rating Curve= 0 ,0
Exp/Cntr(USF)=0,0
Exp/Cntr=0.3,0.1

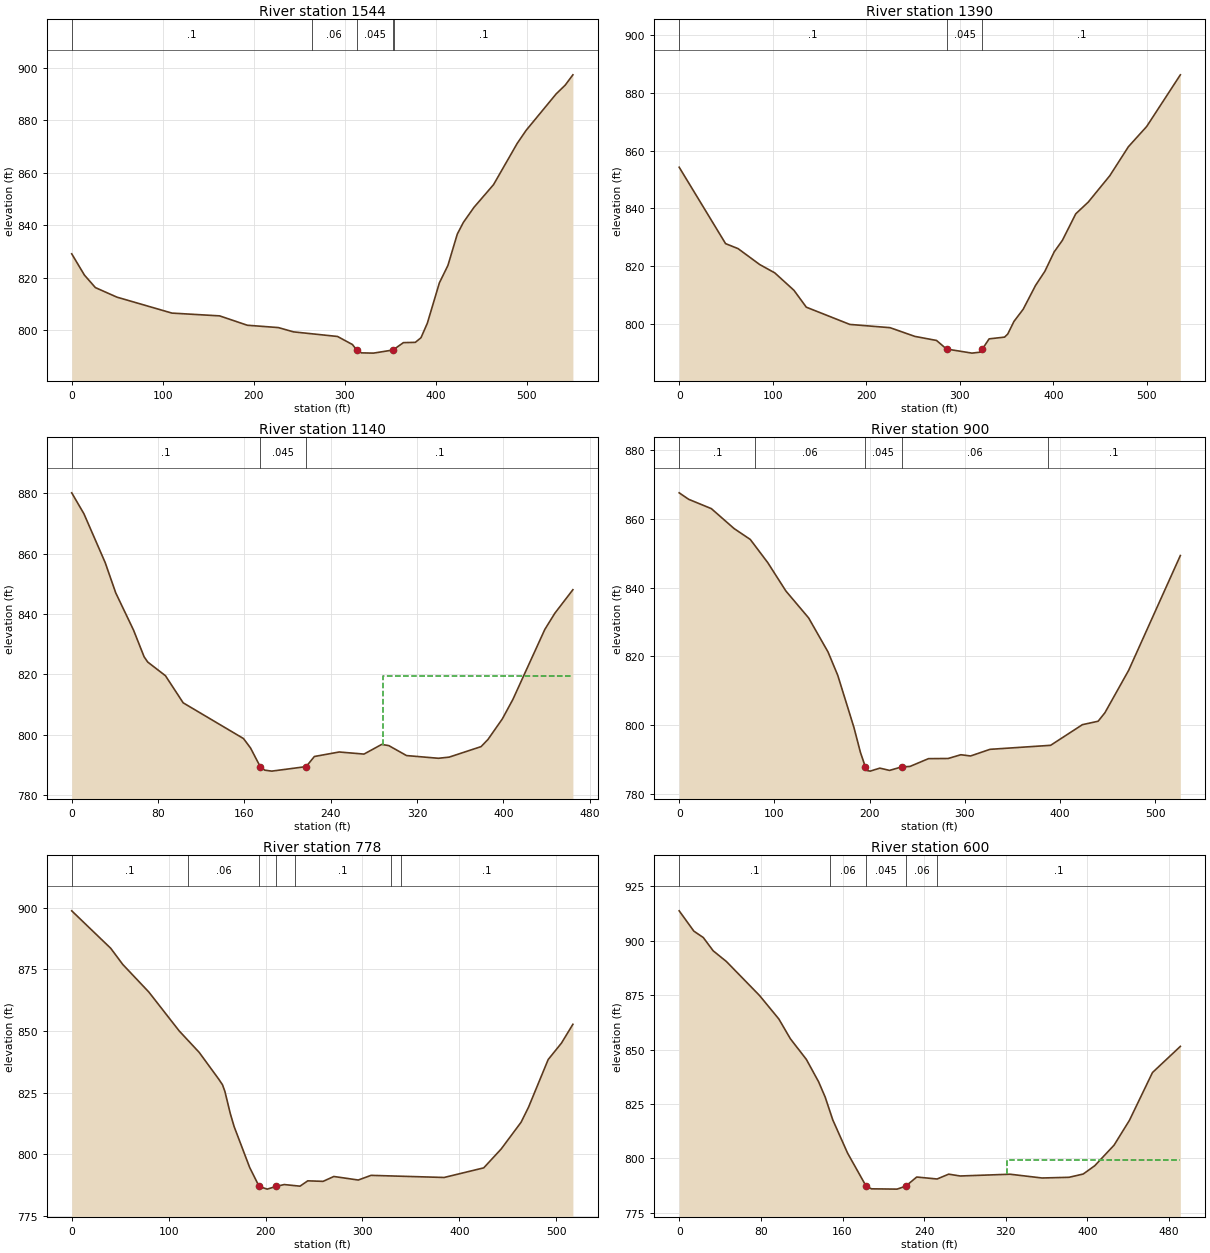
Type RM Length L Ch R = 1 ,1544    ,152.1,154,153.9
XS GIS Cut Line= 4
1659822.98941654531951.9745591961660032.99335219532075.521769592
1660162.67981296532086.2175601711660338.90344262532100.378653477
#Sta/Elev= 30
       0  829.14      14  821.02      26  816.27    49.6  812.64   110.1  806.55
   162.5  805.49   192.9  801.92     227  801.03   243.7  799.39     292  797.64
   308.4  794.57  313.12792.4819   318.3  791.39   331.5  791.29  352.93792.4818
   364.4  795.29   377.5   795.4   383.7  797.15   390.7  802.71   403.9  818.06
   413.3  824.72   423.6  836.66   430.2  841.08   441.9  846.85   463.4  855.51
   489.5  871.29   499.3  876.25   532.2   890.1   542.1  893.43   550.6  897.38
#Mann= 5 ,-1,0
       0      .1       0  263.65     .06       0  313.12    .045       0
  352.93     .06       0  353.65      .1       0
Bank Sta=313.12,352.93
XS Rating Curve= 0 ,0
Exp/Cntr(USF)=0,0
Exp/Cntr=0.3,0.1

Type RM Length L Ch R = 1 ,1390    ,249,250.1,240.7
XS GIS Cut Line= 3
1659805.69095212532249.0957774941659994.60535322532220.217142931
1660336.33586222532264.738371216
#Sta/Elev= 30
       0  854.26    49.6  827.78    62.9  826.06    86.1  820.53   102.2  817.64
   122.7   811.6   135.9  805.75   182.4  799.78   225.4  798.65   251.9  795.63
   275.1  794.22  285.77  791.25     313  789.83   321.4  790.15  324.06791.2524
   331.3  794.77   347.8  795.38   351.2  796.44   357.8   800.8   367.7  805.04
   380.9  813.29   390.9  818.21   400.8   824.9   409.6  828.92   423.9  838.12
   437.2  842.16   460.3  851.33   480.2  861.38   499.7  868.38   535.7  886.29
#Mann= 3 ,-1,0
       0      .1       0  285.77    .045       0  324.06      .1       0
Bank Sta=285.77,324.06
XS Rating Curve= 0 ,0
Exp/Cntr(USF)=0,0
Exp/Cntr=0.3,0.1

Type RM Length L Ch R = 1 ,1140    ,241.8,240.3,233.2
XS GIS Cut Line= 2
1659853.36154316532483.2936519161660317.04501202532455.760614034
#Sta/Elev= 30
       0   880.1    11.3  873.18      31  857.03    40.8  846.99    57.3  834.67
    67.1  825.84    70.4  824.12    86.9  819.57   103.3  810.61   159.2  798.79
   165.7  795.68  174.72789.5014   178.9  788.33   185.4  788.01  217.27789.5035
   224.9  792.85   247.9  794.34   270.9  793.65   287.3  796.85   293.9  796.45
   310.3  793.16   339.9  792.26   349.8  792.64   379.4  796.12   385.8  798.49
   399.1  805.29   408.9  811.75   438.5  834.91   447.8  840.27   464.5  848.04
#Mann= 3 ,-1,0
       0      .1       0  174.72    .045       0  217.27      .1       0
#XS Ineff= 2 , 0
                           288.3          819.44
Permanent Ineff=
       F       F
Bank Sta=174.72,217.27
XS Rating Curve= 0 ,0
Exp/Cntr(USF)=0,0
Exp/Cntr=0.3,0.1

Type RM Length L Ch R = 1 ,900     ,126.4,121.9,117
XS GIS Cut Line= 6
1659894.35265134532759.1811702551659978.63529117532735.670062423
1660050.95109142532715.7836192551660147.37183034532689.268908501
1660219.68763059532669.3844338361660393.55052258532595.400290739
#Sta/Elev= 30
       0  867.59      10   865.7    33.8  862.99    57.7  857.19    74.7  854.02
    93.1  847.26   112.1  839.02     136  831.18   156.4  821.26   166.6  814.47
   183.6   799.3   190.4  792.06  195.49 787.901   197.2  786.78   200.6   786.6
   210.8  787.47     221  786.81   233.6787.8221   242.5  787.97   261.9  790.23
   282.6  790.28   295.9  791.37   306.1  791.01   326.5  792.94   390.2  794.11
   423.6  800.12   440.1  801.12   447.2  803.57   472.2  815.94   526.5  849.34
#Mann= 5 ,-1,0
       0      .1       0      80     .06       0  195.49    .045       0
   233.6     .06       0   387.5      .1       0
Bank Sta=195.49,233.6
XS Rating Curve= 0 ,0
Exp/Cntr(USF)=0,0
Exp/Cntr=0.3,0.1

Type RM Length L Ch R = 1 ,778     ,174.8,178.1,178.6
XS GIS Cut Line= 2
1659986.37726733532927.0993704861660410.37682247532630.972697054
#Sta/Elev= 30
       0  898.66    40.3  883.46    52.7  876.92    79.6  865.74   110.9     850
   131.6  841.27   151.6  830.51   155.6  828.18   158.1  825.44   163.6  816.56
   167.6  811.23   183.6  794.69   193.4  786.98   201.7  785.88  210.79786.9738
   219.3  787.73   235.6  787.08   243.6  789.24   259.4  789.03   270.5     791
   295.7  789.57   308.9  791.46   384.3   790.6   425.2   794.5   443.2  802.15
   463.7  812.97   471.4  819.06   491.7   838.4   505.4  845.06   517.2  852.68
#Mann= 7 ,-1,0
       0      .1       0     120     .06       0   193.4    .045       0
  210.79     .06       0     230      .1       0     330     .06       0
     340      .1       0
Bank Sta=193.4,210.79
XS Rating Curve= 0 ,0
Exp/Cntr(USF)=0,0
Exp/Cntr=0.3,0.1

Type RM Length L Ch R = 1 ,600     ,200.3,198.1,200.5
XS GIS Cut Line= 6
1660078.49762426 533054.438125671660154.40003151533010.905732423
1660219.45895651 532973.592158751660306.20484601532923.840945929
1660371.64926893532887.1996150021660505.15291863532811.351772311
#Sta/Elev= 30
       0  913.79    14.4  904.44    23.6  901.52    33.3  895.41    46.3  890.47
    78.7  874.87    97.6  864.09   108.9  854.99   124.6  845.48   136.6  835.18
     143   828.2   150.5  817.65     165  802.38  183.11787.2267   188.4  785.98
   213.5  785.84  222.02787.2252   232.7   791.4   252.7   790.5     264  792.72
   275.3  791.88   324.2  792.69   355.5  790.96     382  791.28   395.8  792.78
   407.1  796.58     426  806.02   441.1  817.46   463.7  839.45     491  851.47
#Mann= 5 ,-1,0
       0      .1       0   147.5     .06       0  183.11    .045       0
  222.02     .06       0   252.5      .1       0
#XS Ineff= 2 , 0
                          320.94          799.16
Permanent Ineff=
       F       F
Bank Sta=183.11,222.02
XS Rating Curve= 0 ,0
Exp/Cntr(USF)=0,0
Exp/Cntr=0.3,0.1

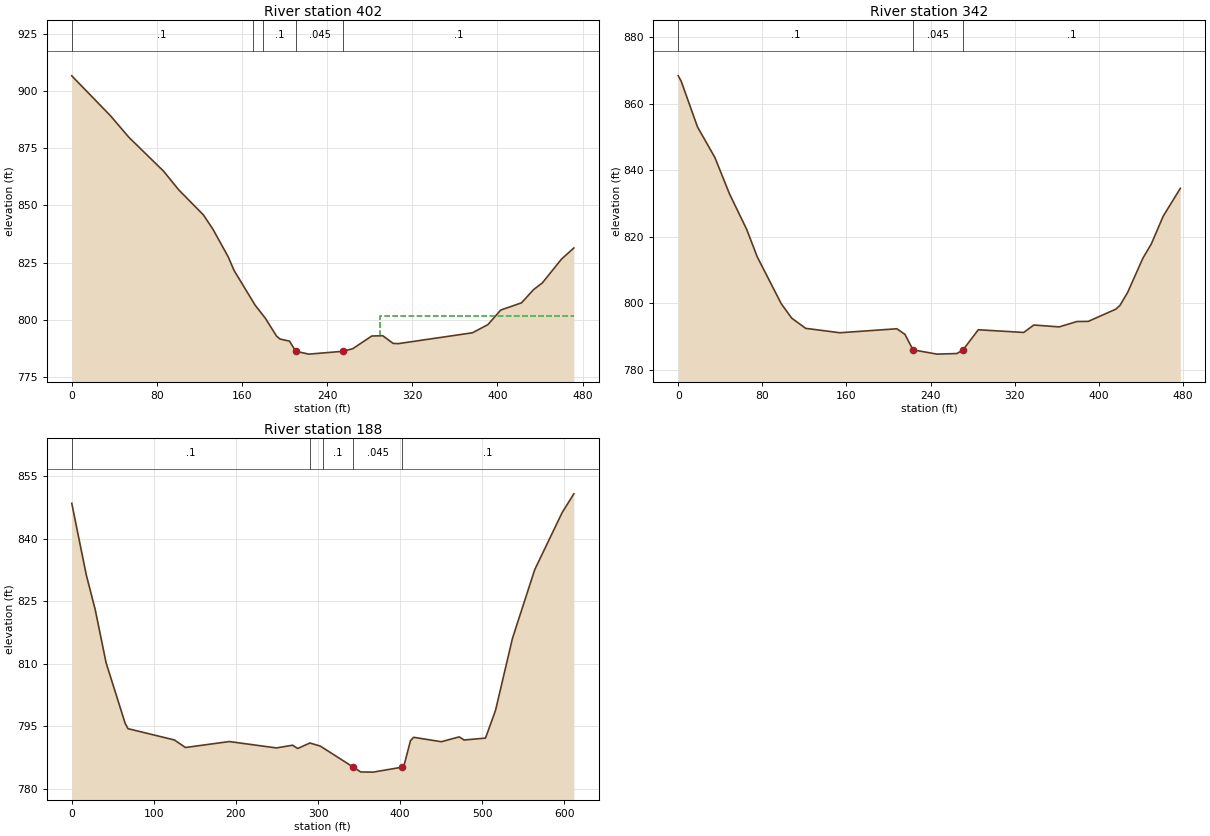
Type RM Length L Ch R = 1 ,402     ,55.8,59.7,55.2
XS GIS Cut Line= 5
1660153.07467023533154.0213287231660347.54450249533127.561050343
1660444.81665429533069.9151407991660510.26107721533033.273809872
1660586.74747279532990.759131125
#Sta/Elev= 30
       0  906.63    36.3  889.21    53.7  879.75    86.3  864.94   100.4  856.84
   123.7  845.84   132.7  839.55     147   827.5   152.5  821.56   172.4  806.31
     182  800.61   192.3  792.94   195.6  791.58   204.6  790.65   210.5 786.222
   222.8  784.97   255.1786.2235   264.1  787.36   281.9  792.89   292.3  793.01
   301.9  789.67   306.7  789.55   376.5   794.3     391  797.85   403.1  804.24
   422.6  807.39   433.9  813.15   442.2  816.11   460.2  826.51   471.8  831.38
#Mann= 5 ,-1,0
       0      .1       0     170     .06       0     180      .1       0
   210.5    .045       0   255.1      .1       0
#XS Ineff= 2 , 0
                          289.89          801.51
Permanent Ineff=
       F       F
Bank Sta=210.5,255.1
XS Rating Curve= 0 ,0
Exp/Cntr(USF)=0,0
Exp/Cntr=0.3,0.1

Type RM Length L Ch R = 1 ,342     ,149.3,154.4,153.7
XS GIS Cut Line= 6
1660183.33767434533196.5649721781660340.73983317533194.762473403
 1660377.8075066533170.104693798 1660475.0796584533112.458784254
1660540.52408132533075.817453327 1660617.0104769 533033.30277458
#Sta/Elev= 30
       0  868.37     2.8  866.77    18.3  853.02    34.9  843.78    48.7  832.91
    65.1  822.18    75.2  813.89    97.9  799.87   107.9  795.49   121.2  792.42
   153.7  791.09   207.9  792.29   215.6  790.61223.2806785.9493   246.1  784.66
   265.1  784.84270.8206785.9351   285.4  791.99   328.6  791.18   338.2  793.42
   362.3  792.85   379.2  794.47     390  794.51   416.2  798.19   420.2  799.36
   427.4  803.22   441.9  813.51     450  817.86   461.2  826.14   477.5  834.52
#Mann= 3 ,-1,0
       0      .1       0223.2806    .045       0270.8206      .1       0
Bank Sta=223.2806,270.8206
XS Rating Curve= 0 ,0
Exp/Cntr(USF)=0,0
Exp/Cntr=0.3,0.1

Type RM Length L Ch R = 1 ,188     ,,,
XS GIS Cut Line= 4
1660171.23949905533232.3918272531660462.45446088533285.108447199
1660570.34864944533222.8280619351660661.39557701533054.967221362
#Sta/Elev= 30
       0   848.5    17.7   831.3    28.5  823.04    41.8  810.24    65.1  795.65
    68.5  794.41     125   791.7   138.5  789.89   191.8  791.32   249.2  789.79
     269  790.44   275.2  789.65     290  790.97   302.7  790.23  343.02785.1605
   351.9  784.02   367.1  783.98  402.04 785.161   404.9  785.74   412.5  791.51
   416.3  792.34   450.1  791.28   471.9  792.44   477.8  791.69   503.9  792.15
   516.1  798.79   536.7  816.06   563.8  832.55   597.2  846.26   611.5  850.78
#Mann= 5 ,-1,0
       0      .1       0     290     .05       0  305.95      .1       0
  343.02    .045       0  402.04      .1       0
Bank Sta=343.02,402.04
XS Rating Curve= 0 ,0
Exp/Cntr(USF)=0,0
Exp/Cntr=0.3,0.1
LCMann Table=0

Chan Stop Cuts=-1
Use User Specified Reach Order=0
Composite Channel Slope=5